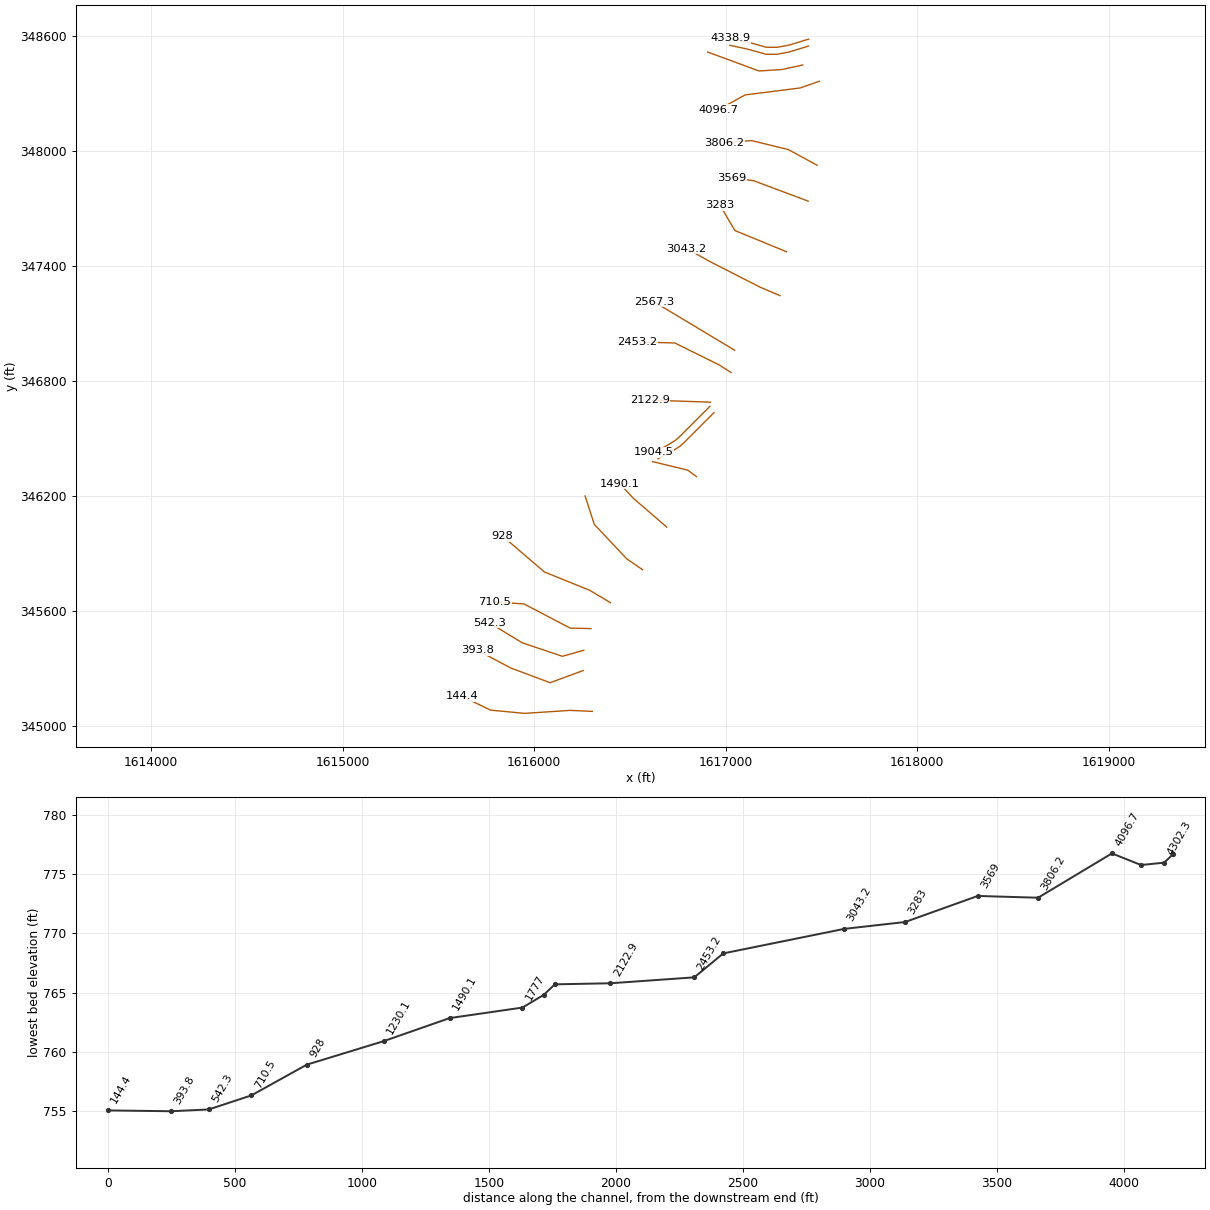
HEC-RAS study WLNUTFRK.prj: WLNUTFRK

--- WLNUTFRK.g01 (geometry) --- (continued)

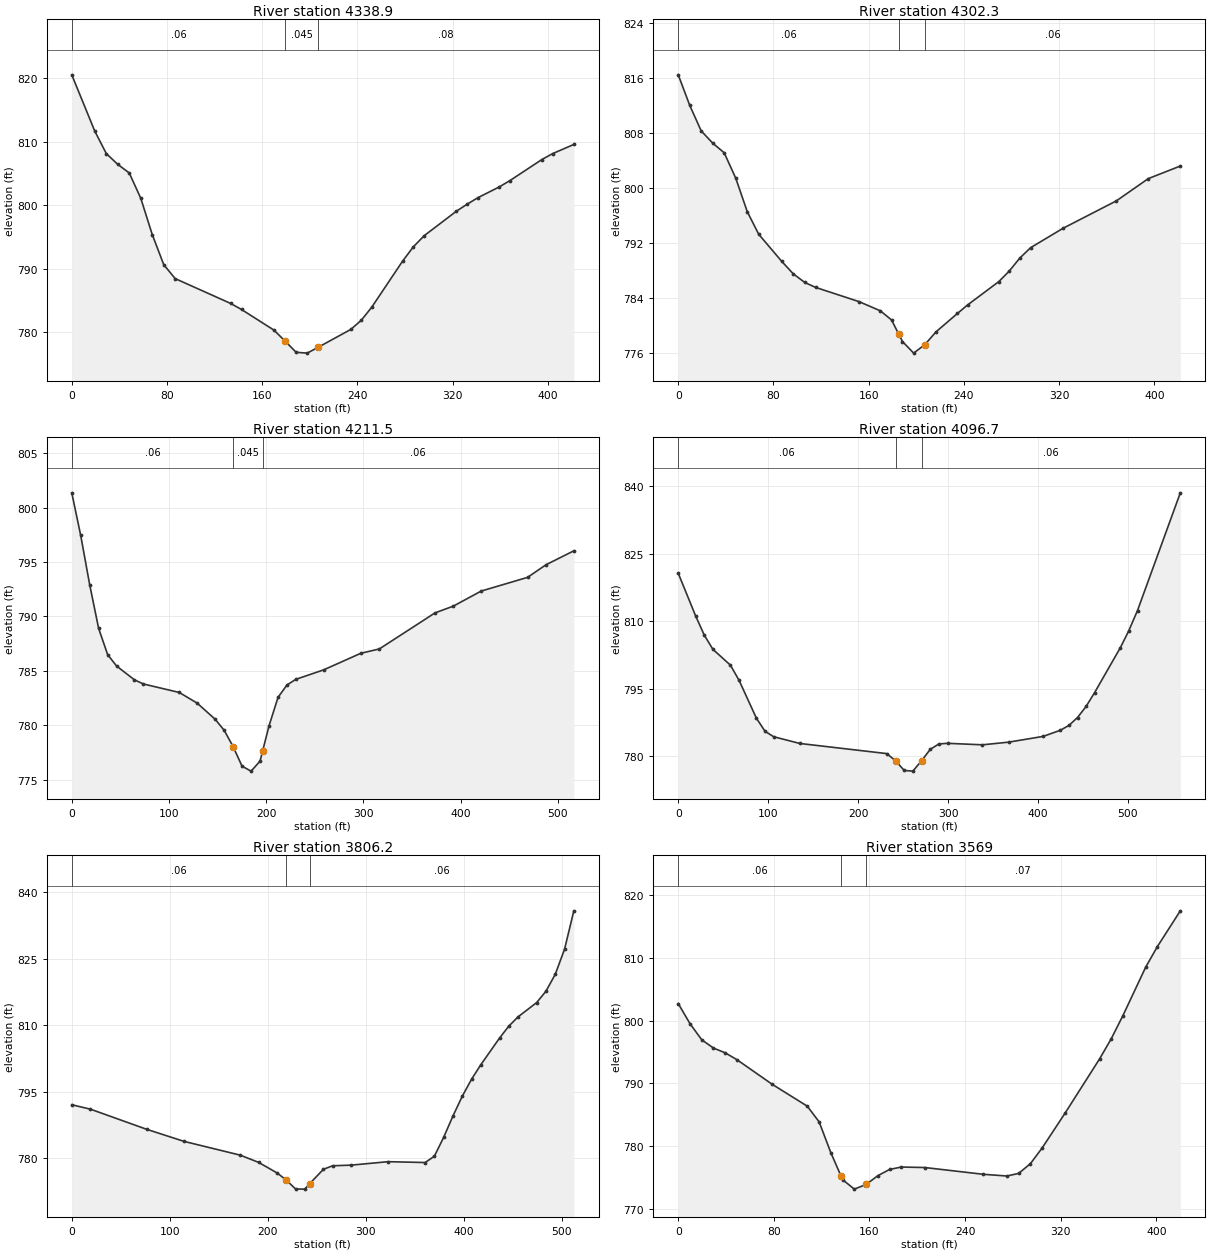
Type RM Length L Ch R = 1 ,4338.9  ,36.6,36.6,36.6
XS GIS Cut Line= 6
     1617433.923      348585.037     1617332.361      348553.787
     1617269.861      348542.068     1617213.871      348542.068
     1617120.121       348568.11     1617023.767      348588.943
#Sta/Elev= 30
       0  820.52    19.3  811.67      29  808.13    38.6  806.43    48.3  805.07
      58  801.07    67.6  795.38    77.3  790.62    86.9  788.44   133.5  784.53
   142.6  783.58   169.8  780.34   179.2  778.61   188.5  776.84   197.8  776.71
   207.2  777.65   234.5  780.45   243.2  781.88   251.9  783.91     278  791.21
     287  793.45   296.1   795.2   323.2  799.06   332.2  800.16   341.2  801.18
   359.1  802.87   368.1  803.87   394.9  807.18   403.9  808.11   421.8  809.56
#Mann= 3 , 0 , 0
       0     .06       0   179.2    .045       0   207.2     .08       0
Bank Sta=179.2,207.2
XS Rating Curve= 0 ,0
Exp/Cntr=0.3,0.1

Type RM Length L Ch R = 1 ,4302.3  ,89.2,90.8,92.3
XS GIS Cut Line= 6
     1617432.621      348548.579     1617331.059      348517.329
     1617268.559       348505.61     1617212.569       348505.61
     1617118.819      348531.651     1617022.465      348552.485
#Sta/Elev= 30
       0  816.49     9.7  812.03    19.3  808.32      29  806.54    38.6  805.14
    48.3  801.45      58  796.56    67.6  793.28    86.9  789.34    96.6  787.52
   106.3  786.26   115.4  785.54   151.7  783.48   169.8  782.13   179.2   780.8
  185.12778.7795   188.4  777.66   197.8  775.97   207.2  777.21   216.5  779.06
   234.5  781.74   243.2     783   269.3  786.38     278   787.9     287  789.82
   296.1  791.33   323.2  794.14   368.1  798.14   394.9  801.38   421.8  803.21
#Mann= 3 , 0 , 0
       0     .06       0  185.12    .045       0   207.2     .06       0
Bank Sta=185.12,207.2
XS Rating Curve= 0 ,0
Exp/Cntr=0.3,0.1

Type RM Length L Ch R = 1 ,4211.5  ,113.4,114.8,116
XS GIS Cut Line= 4
     1617402.673       348449.62       1617294.6      348426.183
     1617174.809       348418.37     1616906.579      348517.329
#Sta/Elev= 30
       0  801.35     9.2  797.43    18.4  792.92    27.6   788.9    36.9  786.48
    46.1  785.43    64.5  784.16    73.7  783.78   110.6     783     129  782.02
   147.5  780.54   156.8  779.52     166  778.02   175.2  776.22   184.5  775.77
   193.7  776.69   196.4  777.64   202.9  779.93   212.2  782.55   221.4  783.69
   230.6  784.21   259.2  785.08   297.3   786.6   316.4     787   373.6  790.31
   392.6  790.94   421.2  792.32   468.9  793.58   487.9  794.74   516.5  796.02
#Mann= 3 , 0 , 0
       0     .06       0     166    .045       0   196.4     .06       0
Bank Sta=166,196.4
XS Rating Curve= 0 ,0
Exp/Cntr=0.3,0.1

Type RM Length L Ch R = 1 ,4096.7  ,298.7,290.5,281.9
XS GIS Cut Line= 4
     1617489.913      348364.985     1617389.652      348329.829
     1617101.892       348293.37     1616959.965      348215.245
#Sta/Elev= 30
       0  820.67    19.3  811.22      29  806.92    38.6  803.77      58  800.28
    67.6  796.92    86.9  788.51    96.6  785.57   106.2  784.38   135.2  782.89
   231.9  780.64   241.6  779.05   251.3   776.9   260.9  776.75   270.6  779.06
   280.3   781.6     290  782.79   299.6  782.92   338.3  782.59   367.3  783.18
   405.8  784.46   424.9  785.82   434.4  786.89     444  788.65   453.5   791.1
     463  794.18   491.6  804.14   501.1  807.95   510.7   812.4   558.3  838.52
#Mann= 3 , 0 , 0
       0     .06       0   241.6    .045       0   270.6     .06       0
Bank Sta=241.6,270.6
XS Rating Curve= 0 ,0
Exp/Cntr=0.3,0.1

Type RM Length L Ch R = 1 ,3806.2  ,240,237.3,234.9
XS GIS Cut Line= 4
     1617478.194      347926.183     1617327.152      348008.214
     1617134.444      348055.089     1616992.517       348043.37
#Sta/Elev= 30
       0  792.04    19.1  791.04    76.4  786.51   114.6  783.78   171.9  780.68
   190.8  779.04   209.7  776.65   219.1  775.03   228.5  773.04     238  773.01
   242.8  774.22   256.9  777.48   266.3  778.28   285.2  778.42     323   779.2
   360.8  779.01   370.2  780.43   379.7   784.7   389.2  789.52   398.7  793.97
   408.2  797.81   417.7  801.09   436.7  807.07   446.2  809.77   455.6  811.86
   474.6  815.08   484.1  817.64   493.6  821.45   503.1  827.11   512.6  835.78
#Mann= 3 , 0 , 0
       0     .06       0   219.1    .045       0   242.8     .06       0
Bank Sta=219.1,242.8
XS Rating Curve= 0 ,0
Exp/Cntr=0.3,0.1

Type RM Length L Ch R = 1 ,3569    ,286.6,286,285.3
XS GIS Cut Line= 3
     1617431.319      347738.683     1617146.163      347845.454
     1617031.579      347861.079
#Sta/Elev= 30
       0  802.72     9.8  799.53    19.6  796.96    29.5  795.63    39.3  794.87
    49.1  793.78    78.6  789.86     108  786.37   117.9  783.87   127.7  778.96
   136.3   775.2   137.5  774.68   147.3  773.16   157.2   773.9     167   775.3
   176.8  776.29   186.6  776.68   206.3   776.6   255.4  775.52     275  775.25
   284.8  775.66   294.7  777.22   304.5  779.72   323.8   785.3   352.7  793.95
   362.3  797.11     372  800.77   391.2  808.54   400.9  811.79   420.1  817.49
#Mann= 3 , 0 , 0
       0     .06       0   136.3    .045       0   157.2     .07       0
Bank Sta=136.3,157.2
XS Rating Curve= 0 ,0
Exp/Cntr=0.3,0.1

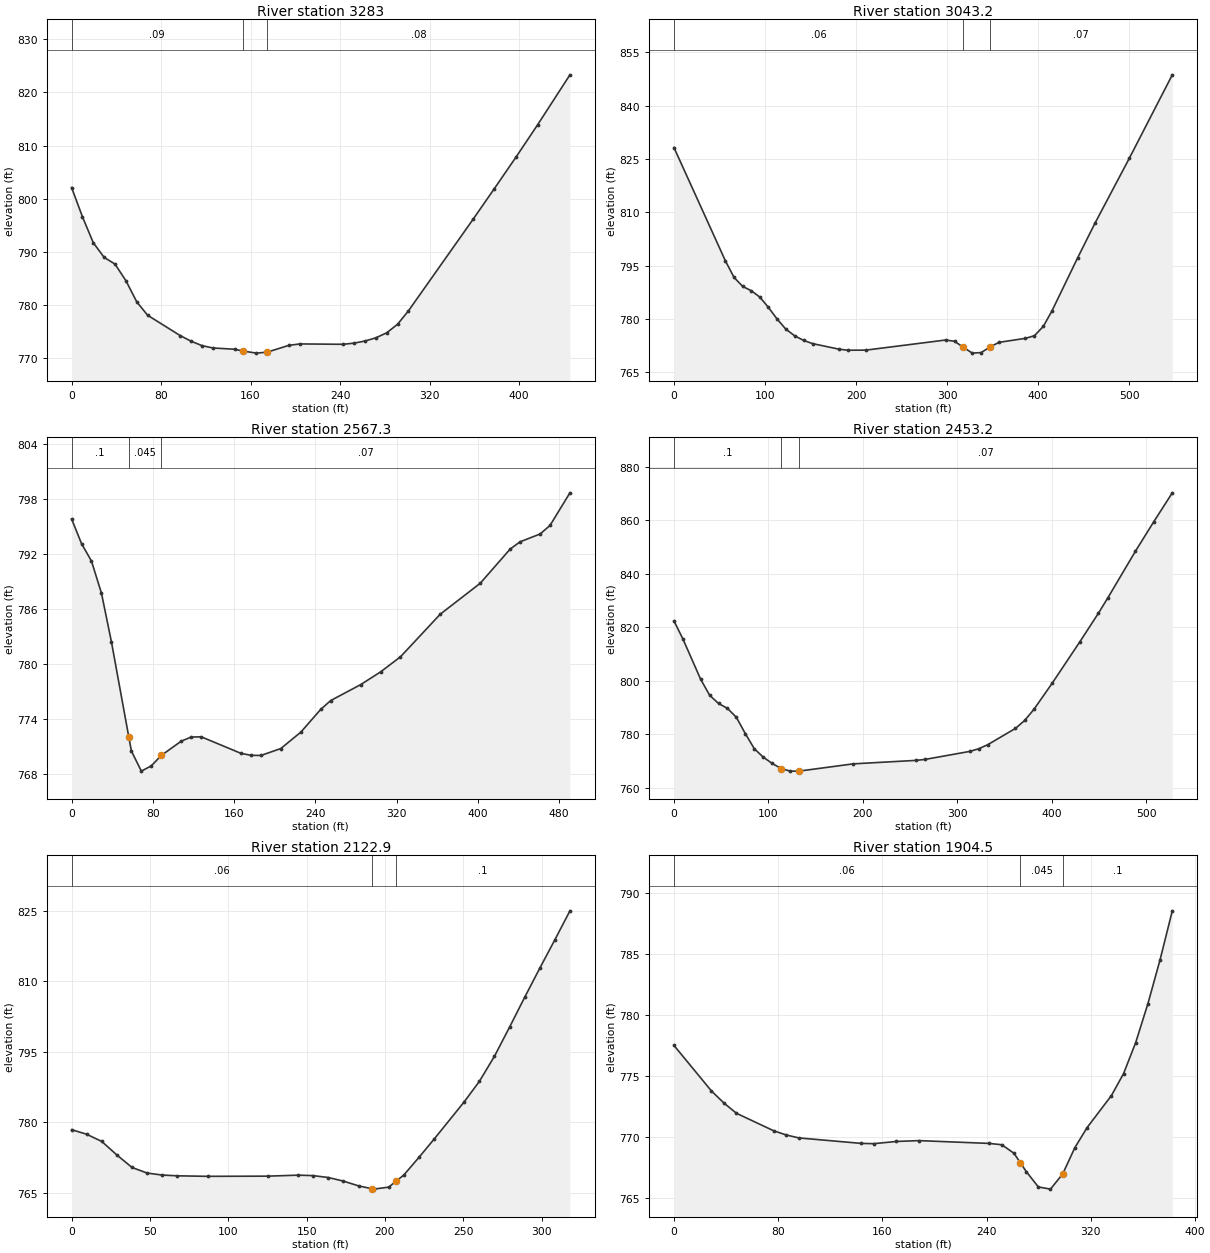
Type RM Length L Ch R = 1 ,3283    ,241.4,239.8,238.1
XS GIS Cut Line= 3
     1617318.038       347474.36     1617048.507      347585.037
     1616970.382      347717.849
#Sta/Elev= 30
       0   802.1     9.7  796.61    19.4  791.72    29.1  788.97    38.8  787.71
    48.6  784.57    58.3  780.59      68  778.08    97.1  774.26   106.8   773.2
   116.6  772.37   126.3  771.93   145.7  771.69   153.1  771.36   165.1  770.96
   174.8  771.14   194.2  772.42     204  772.69   242.8  772.62   252.5  772.84
   262.2  773.23     272  773.84   281.7  774.78   291.4  776.39     301  778.87
   358.8   796.1     378  801.92   397.3  807.83   416.6   813.9   445.5   823.3
#Mann= 3 , 0 , 0
       0     .09       0   153.1    .045       0   174.8     .08       0
Bank Sta=153.1,174.8
XS Rating Curve= 0 ,0
Exp/Cntr=0.3,0.1

Type RM Length L Ch R = 1 ,3043.2  ,477.5,475.9,473.7
XS GIS Cut Line= 4
     1617284.184      347245.193     1617180.017      347289.464
       1616919.6      347422.276     1616795.902      347491.287
#Sta/Elev= 30
       0  828.21    56.6  796.28      66  791.67    75.5  789.14    84.9  787.94
    94.3  786.14   103.8  783.22   113.2  779.99   122.9  777.11   132.7  775.23
   142.4  773.96   152.2  773.06   181.4  771.48   191.1   771.2   210.6  771.22
   298.3  774.07   308.1  773.72   317.8  772.01   327.6  770.38   337.3  770.54
     347  772.08   356.8  773.41     386  774.54   395.8  775.28   405.5  777.88
     415  782.22   443.3  797.21   462.2  806.88   499.9  825.14   547.2  848.66
#Mann= 3 , 0 , 0
       0     .06       0   317.8    .045       0     347     .07       0
Bank Sta=317.8,347
XS Rating Curve= 0 ,0
Exp/Cntr=0.3,0.1

Type RM Length L Ch R = 1 ,2567.3  ,111.7,114.1,116
XS GIS Cut Line= 2
     1617047.204      346960.037     1616626.632      347212.641
#Sta/Elev= 30
       0  795.86     9.8  793.16    19.6  791.25    29.4  787.75    39.2  782.45
    56.4  771.99    58.9   770.5    68.7  768.31    78.5  768.89    88.3  770.02
   107.9  771.58   117.7  772.03   127.6  772.06   166.8  770.25   176.6  770.04
   186.4  770.02     206  770.78   225.7  772.57   245.3  775.06   255.1  776.02
   284.6  777.76   304.2  779.15   323.8   780.8     363  785.46   402.3  788.83
   431.7  792.56   441.5  793.36   461.2  794.21     471  795.15   490.6  798.71
#Mann= 3 , 0 , 0
       0      .1       0    56.4    .045       0    88.3     .07       0
Bank Sta=56.4,88.3
XS Rating Curve= 0 ,0
Exp/Cntr=0.3,0.1

Type RM Length L Ch R = 1 ,2453.2  ,320.2,330.2,340.8
XS GIS Cut Line= 4
     1617028.632      346843.934     1616964.613      346884.082
     1616734.578      346998.014     1616539.265       347003.44
#Sta/Elev= 30
       0  822.38     9.4  815.69    28.3  800.56    37.8  794.62    47.2  791.55
    56.7   789.7    66.1  786.38    75.6  780.28    85.1  774.65    94.6   771.5
   104.1  769.14   113.6  767.24   123.1  766.29   132.6   766.3   189.7     769
   256.2   770.3   265.7  770.65   313.2  773.65   322.8  774.65   332.3  776.16
   361.6  782.24   371.4  785.22   381.1  789.31   400.7  799.21     430  814.67
   449.5  825.26   459.3  830.89   488.6  848.35   508.1   859.4   527.7  870.18
#Mann= 3 , 0 , 0
       0      .1       0   113.6    .045       0   132.6     .07       0
Bank Sta=113.6,132.6
XS Rating Curve= 0 ,0
Exp/Cntr=0.3,0.1

Type RM Length L Ch R = 1 ,2122.9  ,199.8,218.4,232.6
XS GIS Cut Line= 2
      1616921.21       346688.77     1616603.285       346699.62
#Sta/Elev= 30
       0  778.43     9.6  777.46    19.3  775.92    28.9  773.05    38.6  770.39
    48.2  769.21    57.8  768.78    67.5  768.62    86.8  768.51   125.3  768.55
   144.6  768.76   154.2  768.66   163.9  768.26   173.5  767.49   183.2  766.48
     192  765.85   192.8  765.79   202.4  766.21     207  767.44   212.1   768.8
   221.7  772.53   231.4  776.42   250.6  784.34   260.3   788.7   269.9  794.02
   279.6  800.25   289.2  806.56   298.8  812.72   308.5  818.81   318.1  824.95
#Mann= 3 , 0 , 0
       0     .06       0     192    .045       0     207      .1       0
Bank Sta=192,207
XS Rating Curve= 0 ,0
Exp/Cntr=0.3,0.1

Type RM Length L Ch R = 1 ,1904.5  ,48.5,43.9,43.2
XS GIS Cut Line= 6
     1616917.955      346667.068     1616809.448      346558.561
      1616760.62      346509.733     1616738.918      346490.202
     1616691.175      346460.905     1616624.986      346426.183
#Sta/Elev= 27
       0  777.49    28.8  773.75    38.4  772.76      48  771.92    76.7  770.48
    86.3  770.14    95.9   769.9   143.9  769.45   153.4  769.43   170.7  769.61
     188  769.68     242  769.45   251.7  769.34     261  768.64   265.9  767.86
   270.4  767.14   279.7  765.88     289   765.7   298.4  766.95   307.7   769.1
   317.1  770.75   335.8  773.38   345.1  775.18   354.4  777.72   363.8  780.92
   373.1  784.51   382.5  788.53
#Mann= 3 , 0 , 0
       0     .06       0   265.9    .045       0   298.4      .1       0
Bank Sta=265.9,298.4
XS Rating Curve= 0 ,0
Exp/Cntr=0.3,0.1

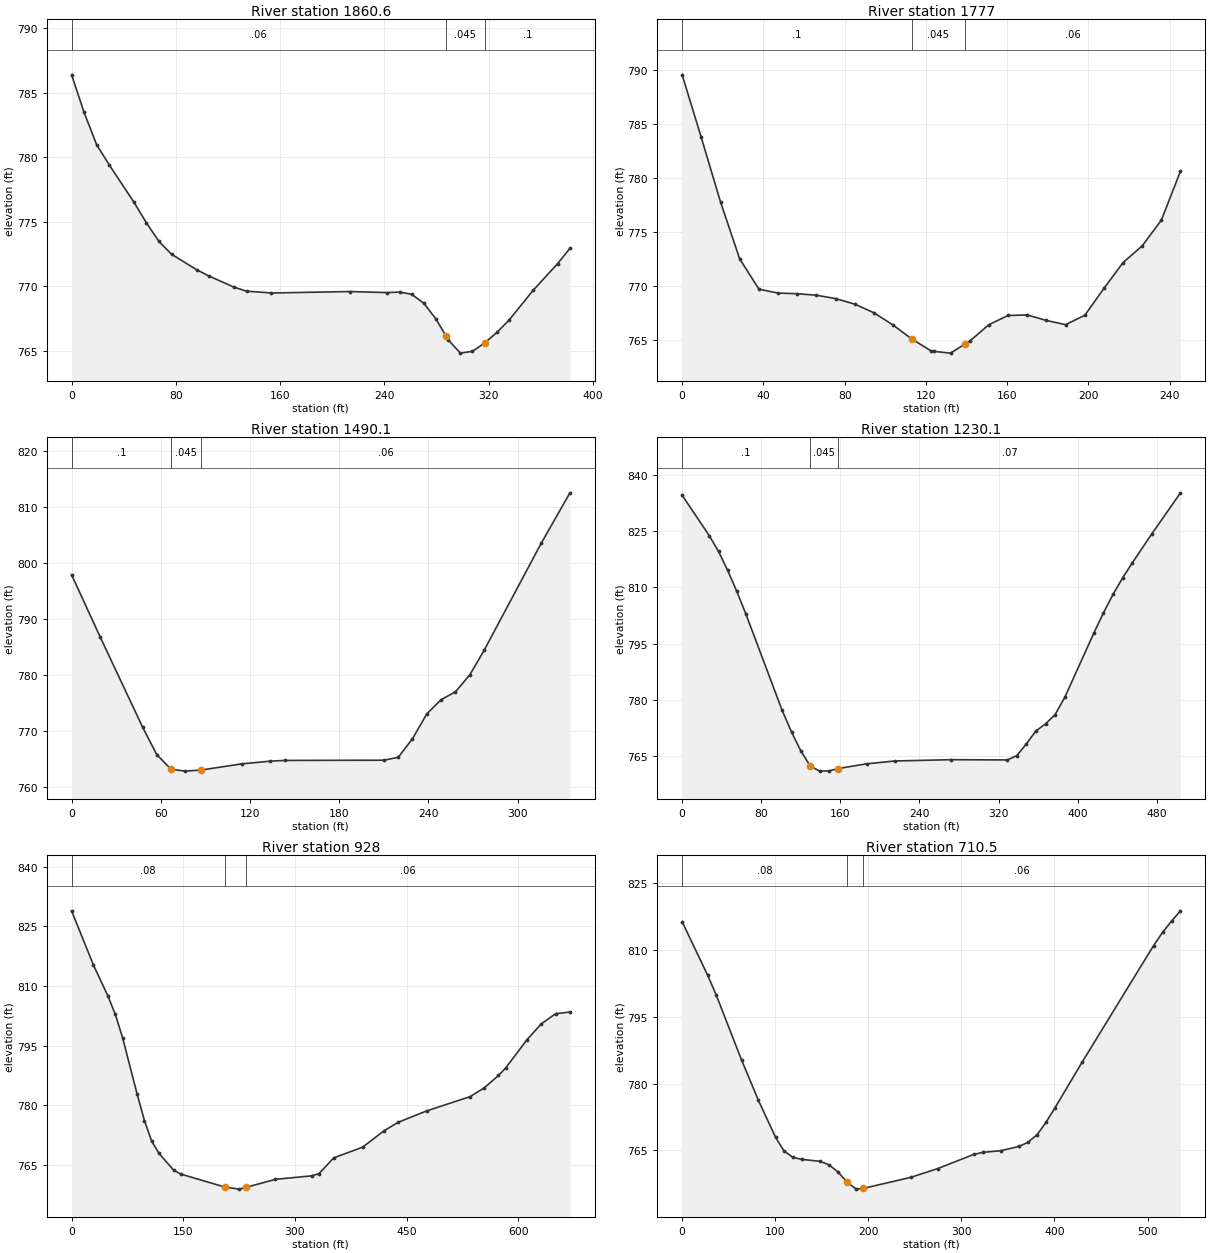
Type RM Length L Ch R = 1 ,1860.6  ,102.2,83.6,65.4
XS GIS Cut Line= 6
     1616939.656      346634.516     1616831.149      346526.009
     1616782.321      346477.181      1616760.62       346457.65
     1616712.877      346428.353     1616646.687      346393.631
#Sta/Elev= 29
       0  786.37     9.6  783.46    19.2  780.96    28.8  779.41      48  776.48
    57.5  774.89    67.1  773.46    76.7  772.47    95.9  771.28   105.5  770.78
   124.7  769.92   134.3  769.61   153.4  769.47   213.9  769.58     242   769.5
   251.7  769.54     261  769.37   270.4  768.67   279.7  767.45   287.4  766.13
     289  765.85   298.4  764.81   307.7  764.95   317.1   765.6   326.4  766.41
   335.8  767.37   354.4  769.69   373.1  771.75   382.5  772.93
#Mann= 3 , 0 , 0
       0     .06       0   287.4    .045       0   317.1      .1       0
Bank Sta=287.4,317.1
XS Rating Curve= 0 ,0
Exp/Cntr=0.3,0.1

Type RM Length L Ch R = 1 ,1777    ,297.4,286.8,276.4
XS GIS Cut Line= 3
     1616847.425      346300.315     1616801.852      346333.952
     1616618.475       346378.44
#Sta/Elev= 29
       0  789.55     9.4  783.75    18.9  777.75    28.3  772.49    37.8  769.67
    47.2  769.31    56.6  769.25    66.1  769.11    75.5   768.8      85  768.28
    94.4  767.48   103.8  766.35   113.2  765.03   122.7  763.93   124.1   763.9
   132.1  763.74   139.1  764.57   141.6  764.86     151  766.38   160.4  767.23
   169.9  767.28   179.3  766.77   188.7  766.38   198.2  767.25   207.6  769.74
     217  772.13   226.5   773.7   235.9  776.08   245.3  780.62
#Mann= 3 , 0 , 0
       0      .1       0   113.2    .045       0   139.1     .06       0
Bank Sta=113.2,139.1
XS Rating Curve= 0 ,0
Exp/Cntr=0.3,0.1

Type RM Length L Ch R = 1 ,1490.1  ,262.4,260.1,257.7
XS GIS Cut Line= 3
      1616692.26      346036.643     1616518.649      346186.382
     1616445.949      346263.422
#Sta/Elev= 20
       0  797.89    19.1  786.87    47.8  770.68    57.3   765.8    66.9  763.18
    76.4  762.85      87  763.04   114.6  764.15   133.7  764.63   143.3  764.76
   210.2   764.8   219.7  765.32   229.3  768.63   238.9  773.06   248.5  775.59
   258.2  777.01   267.8  780.02   277.4  784.38   315.9  803.53   335.2  812.52
#Mann= 3 , 0 , 0
       0      .1       0    66.9    .045       0      87     .06       0
Bank Sta=66.9,87
XS Rating Curve= 0 ,0
Exp/Cntr=0.3,0.1

Type RM Length L Ch R = 1 ,1230.1  ,292.1,302,311.9
XS GIS Cut Line= 4
     1616566.739      345813.553     1616483.406      345870.844
     1616314.135      346050.532     1616265.958      346198.969
#Sta/Elev= 30
       0  834.67    27.6  823.78    36.8  819.64      46   814.6    55.2     809
    64.4  802.95   101.1  777.18   110.6  771.36   120.1  766.26   129.6  762.28
   139.1   760.9   148.6  760.96   158.1   761.6   186.6  762.86   215.1  763.61
     272  763.96     329  763.89   338.5  765.05     348  768.14   357.7  771.62
   367.5  773.54   377.2  776.02     387  780.65   416.3  797.78     426  803.18
   435.8  808.17   445.5  812.57   455.3   816.6   474.8  824.26     504  835.31
#Mann= 3 , 0 , 0
       0      .1       0   129.6    .045       0   158.1     .07       0
Bank Sta=129.6,158.1
XS Rating Curve= 0 ,0
Exp/Cntr=0.3,0.1

Type RM Length L Ch R = 1 ,928     ,219.7,217.6,215.1
XS GIS Cut Line= 4
     1616398.771      345641.678     1616289.396      345706.782
     1616053.719      345801.834     1615834.969      345989.334
#Sta/Elev= 30
       0  828.91    29.4  815.27      49  807.41    58.8  802.84    68.5  797.02
    88.1  782.78    97.9  776.15   107.7  770.94   117.5   767.9   137.1  763.69
   146.8   762.7   205.5  759.46     225  758.92   234.8  759.39   273.9  761.38
   322.8  762.27   332.5  762.84   352.1  766.78     391  769.47   419.8   773.6
     439  775.75   477.4  778.62   535.1  782.16   554.3  784.37   573.5   787.5
   583.1  789.38   611.9  796.51   631.1  800.49   650.3  803.04   669.5  803.46
#Mann= 3 , 0 , 0
       0     .08       0   205.5    .045       0   234.8     .06       0
Bank Sta=205.5,234.8
XS Rating Curve= 0 ,0
Exp/Cntr=0.3,0.1

Type RM Length L Ch R = 1 ,710.5   ,164.5,168.2,171.8
XS GIS Cut Line= 4
     1616297.208      345506.261     1616187.833      345508.865
     1615946.948      345635.167     1615793.302      345645.584
#Sta/Elev= 30
       0  816.28    27.4  804.29    36.5  799.92    63.8   785.3      82  776.21
   100.3  767.98   109.4   764.9   119.1  763.43   128.8     763   148.3  762.56
     158  761.76   167.7  760.12   177.4  757.84   187.1  756.33   194.3  756.48
   245.4  758.96   274.5  760.93   313.4  764.12   323.1  764.58   342.5  764.95
     362  765.91   371.7  766.85   381.4  768.54     391  771.34   400.6  774.58
   429.5  784.73   506.5  810.94   516.1  813.88   525.8  816.45   535.4  818.73
#Mann= 3 , 0 , 0
       0     .08       0   177.4    .045       0   194.3     .06       0
Bank Sta=177.4,194.3
XS Rating Curve= 0 ,0
Exp/Cntr=0.3,0.1

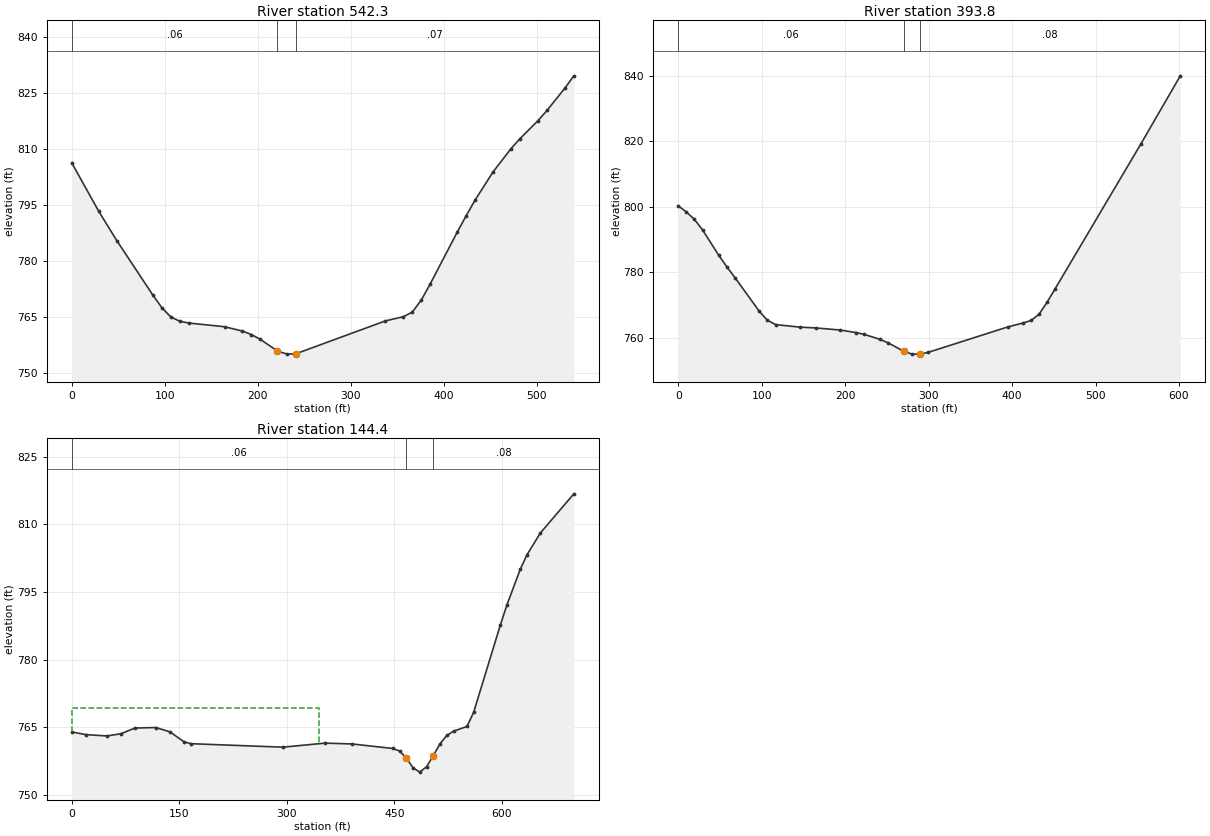
Type RM Length L Ch R = 1 ,542.3   ,149.2,148.5,147.6
XS GIS Cut Line= 4
     1616259.448       345392.98     1616147.469       345361.73
     1615937.833      345432.042     1615764.656      345537.511
#Sta/Elev= 30
       0  806.25    29.1  793.27    48.4   785.5    87.2  770.93    96.9  767.55
   106.6  765.06   116.3  763.91   125.9  763.45   164.3  762.46   183.6  761.31
   193.2  760.38   202.8  759.09   221.3  755.97   231.6  755.14   241.2  755.25
   337.4  764.02   356.7  765.14   366.3  766.36     376  769.59   385.6   773.9
   414.6  787.72   424.3  792.12   433.9  796.32   453.2  803.84   472.6  810.09
   482.2  812.74   501.5  817.53   511.2  820.26   530.5  826.24   540.1  829.52
#Mann= 3 , 0 , 0
       0     .06       0   221.3    .045       0   241.2     .07       0
Bank Sta=221.3,241.2
XS Rating Curve= 0 ,0
Exp/Cntr=0.3,0.1

Type RM Length L Ch R = 1 ,393.8   ,242.7,249.4,255.6
XS GIS Cut Line= 4
     1616256.844      345287.511     1616083.666      345223.709
     1615877.937      345300.532     1615703.458       345392.98
#Sta/Elev= 30
       0  800.26     9.7  798.42    19.4  796.12    29.1  792.93    48.6  785.15
    58.3  781.63      68  778.34    97.1  768.07   106.8  765.34   116.6  764.01
   145.7  763.23   165.1  762.98   194.1  762.34   213.2  761.57   222.8  761.02
   241.8   759.5   251.4  758.45   270.5  755.83     280  755.02   288.1  754.99
   289.6  754.99   299.1   755.5   394.6  763.27   413.6  764.53     423  765.28
   432.4   767.2   441.8  770.77   451.2  774.76   554.6  819.28   601.6  839.96
#Mann= 3 , 0 , 0
       0     .06       0   270.5    .045       0   289.6     .08       0
Bank Sta=270.5,289.6
XS Rating Curve= 0 ,0
Exp/Cntr=0.3,0.1

Type RM Length L Ch R = 1 ,144.4   ,64,64.2,64.7
XS GIS Cut Line= 5
     1616303.719      345073.969     1616186.531      345079.178
     1615950.854      345063.553     1615772.469       345080.48
     1615621.427      345153.396
#Sta/Elev= 30
       0  763.97    19.6  763.37    48.9  763.08    68.4  763.56      88  764.83
   117.3  764.94     137  763.98   156.7  761.77   166.5  761.36   294.4  760.59
   353.5  761.49   391.2   761.3   447.8   760.3   457.2  759.75   466.1   758.3
   476.1  756.02   485.5  755.06     495  756.26   504.4  758.74   513.8  761.36
   523.2  763.18   532.7  764.14   551.3  765.18   560.6   768.3   597.9  787.68
   607.2  792.18   625.9   800.1   635.2  803.27   653.8  808.07   700.4  816.73
#Mann= 3 , 0 , 0
       0     .06       0   466.1    .045       0   504.4     .08       0
#XS Ineff= 2 , 0
          344.48  769.25
Permanent Ineff=
       F       F
Bank Sta=466.1,504.4
XS Rating Curve= 0 ,0
Exp/Cntr=0.3,0.1