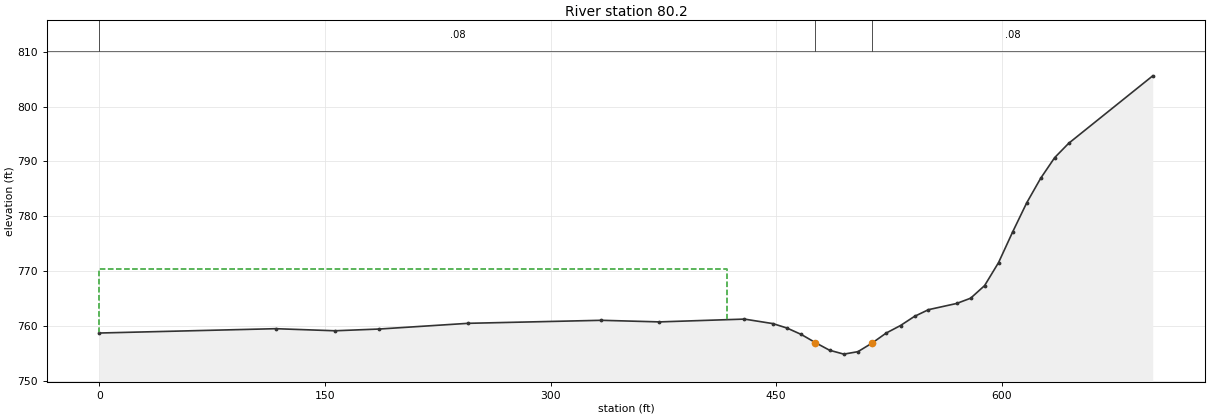
HEC-RAS study WLNUTFRK.prj: WLNUTFRK

--- WLNUTFRK.g01 (geometry) --- (continued)

Type RM Length L Ch R = 1 ,80.2    ,96,80.2,64.4
XS GIS Cut Line= 5
     1616293.302      345015.375     1616176.114      345020.584
     1615940.437      345004.959     1615762.052      345021.886
      1615611.01      345094.803
#Sta/Elev= 30
       0   758.7   117.3  759.49   156.7  759.11   186.2  759.43   245.2  760.47
   333.8  761.02   372.4  760.73   428.9  761.24   447.8  760.42   457.2  759.61
   466.7  758.44   476.1  756.95   485.5  755.56     495  754.85   504.4   755.3
   513.8  756.87   523.2   758.7   532.7  760.07     542  761.74   551.3  762.96
     570  764.09   579.3  765.05   588.6  767.35   597.9  771.56   607.2  777.11
   616.6  782.45   625.9  786.94   635.2   790.7   644.5  793.31   700.4  805.62
#Mann= 3 , 0 , 0
       0     .08       0   476.1    .045       0   513.8     .08       0
#XS Ineff= 2 , 0
          417.56   770.3
Permanent Ineff=
       F       F
Bank Sta=476.1,513.8
XS Rating Curve= 0 ,0
Exp/Cntr=0.3,0.1

Chan Stop Cuts=-1
Use User Specified Reach Order=0
Composite Channel Slope=5

--- WLNUTFRK.g02 (geometry) ---

Geom Title=USGS 10m DEM_old
Program Version=4.10

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
River Reach=WLNUTFRK        ,Main
Reach XY= 30
     1619515.489      354803.991      1619532.85      354541.839
     1619479.031      354253.644     1619335.628      354038.505
     1619481.808      353097.533     1619387.624      352328.002
     1619470.089      351752.915     1619426.687      351407.863
     1618656.577      350565.632     1618416.993      350184.556
     1618129.667      349925.875     1617759.876      349747.924
     1617618.382      349611.639     1617253.799       349057.82
     1617213.868      348853.827     1617274.632      348636.813
     1617214.737      348390.285     1617289.823      347760.945
       1617160.7      347523.314     1616948.026      347357.299
     1616919.815      347133.775     1617013.131       347059.99
     1616889.433      346865.763     1616733.183      346790.893
     1616729.927      346335.164     1616674.589      346142.021
     1616500.978      345934.773     1616205.839      345751.396
      1615987.74      345242.498     1615748.453      344958.228

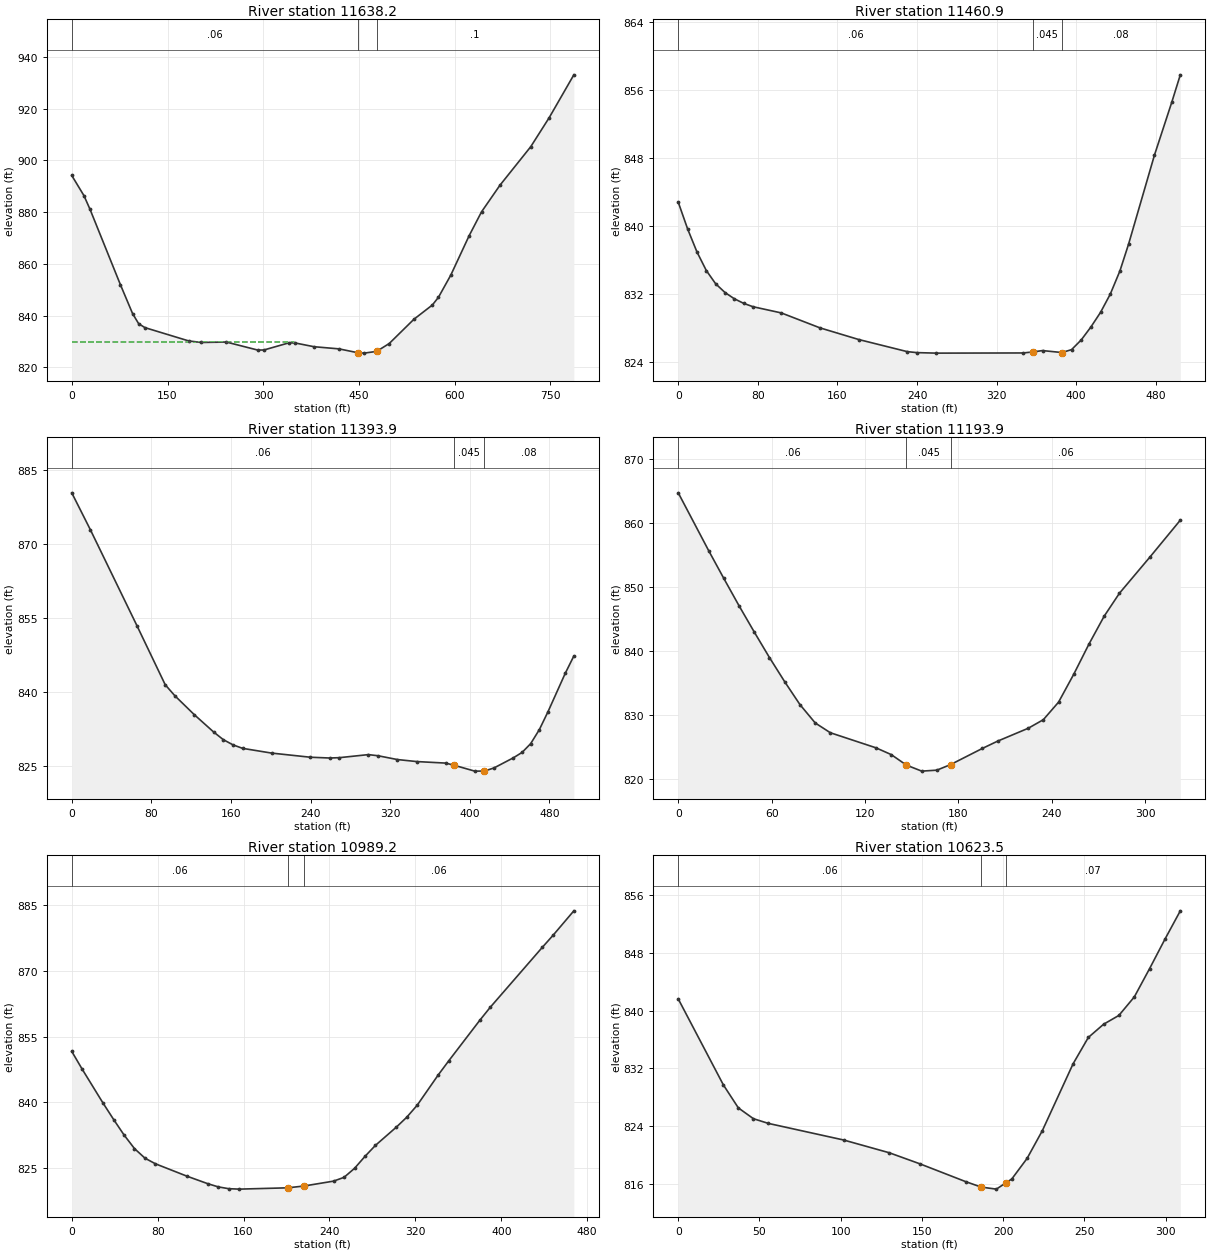
Type RM Length L Ch R = 1 ,11638.2 ,165.4,177.3,187.5
XS GIS Cut Line= 4
     1619946.673       354644.39     1619899.798       354738.14
     1619500.492      354786.751     1619220.978      354785.015
#Sta/Elev= 30
       0  894.19    19.1   886.4    28.6  881.11    76.2  851.99    95.3   840.8
   104.8   836.9   114.6  835.39   183.3  830.24   202.9  829.65   242.2  829.81
   291.2  826.72     301  826.74   340.3  829.51   350.1  829.45   379.5  828.01
   418.8  827.17   448.2  825.68     458  825.53   477.6   826.2   497.3  829.23
     536  838.61   564.9  844.12   574.5  847.12   593.8  855.68   622.7  870.99
     642  880.15   670.9  890.45   719.1  905.33     748  916.55   786.6   933.1
#Mann= 3 , 0 , 0
       0     .06       0   448.2    .045       0   477.6      .1       0
#XS Ineff= 2 , 0
          347.92  829.68
Permanent Ineff=
       F       F
Bank Sta=448.2,477.6
XS Rating Curve= 0 ,0
Exp/Cntr=0.3,0.1

Type RM Length L Ch R = 1 ,11460.9 ,66.8,67,67.4
XS GIS Cut Line= 4
     1619879.847      354709.125      1619785.97      354711.071
      1619461.01      354581.087     1619400.246      354581.087
#Sta/Elev= 29
       0  842.86     9.4  839.72    18.8  837.01    28.2  834.82    37.6  833.26
      47  832.23    56.3   831.5    65.7  830.96    75.1  830.56   103.6  829.83
   142.5  828.07   181.4   826.7     230  825.28   239.7  825.16   259.2   825.1
   346.7  825.12   356.4  825.24   366.1   825.4   385.6  825.17   395.3  825.51
     405  826.65   414.7  828.17   424.4  829.89   434.2  832.04   443.9  834.77
   452.6  837.92   478.6  848.39     496  854.61   504.6  857.84
#Mann= 3 , 0 , 0
       0     .06       0   356.4    .045       0   385.6     .08       0
Bank Sta=356.4,385.6
XS Rating Curve= 0 ,0
Exp/Cntr=0.3,0.1

Type RM Length L Ch R = 1 ,11393.9 ,217.2,200.1,182.4
XS GIS Cut Line= 4
     1619903.588      354652.311     1619809.711      354654.257
     1619484.752      354524.273     1619423.988      354524.273
#Sta/Elev= 30
       0  880.41    18.8  872.88    65.7  853.38    93.9  841.49   103.6  839.25
   123.1  835.42   142.5  831.91   152.2  830.36     162  829.29   171.7  828.58
   200.8  827.62   239.7  826.78   259.2  826.62   268.9  826.69   298.1  827.31
   307.8  827.08   327.2  826.31   346.7   825.9   375.8  825.59   384.5  825.14
     405  823.96   414.7  823.97   424.4  824.61   443.9  826.67   452.6  827.76
   461.2  829.53   469.9  832.37   478.6     836     496  843.82   504.6  847.31
#Mann= 3 , 0 , 0
       0     .06       0   384.5    .045       0   414.7     .08       0
Bank Sta=384.5,414.7
XS Rating Curve= 0 ,0
Exp/Cntr=0.3,0.1

Type RM Length L Ch R = 1 ,11193.9 ,208.3,204.7,201.1
XS GIS Cut Line= 2
      1619653.27      354288.487     1619351.187      354401.335
#Sta/Elev= 27
       0  864.76    19.5  855.73    29.3  851.35    39.1  847.06    48.9  842.94
    58.6  838.97    68.4  835.18    78.2   831.6      88  828.73    97.7   827.2
     127  824.84   136.8  823.78   146.6  822.13   156.4  821.19   166.1  821.34
   174.9  822.21   195.4  824.75   205.2  825.89   224.8   827.9   234.5  829.24
   244.3  831.99   254.1  836.38   263.8  841.07   273.6  845.45   283.4  849.04
   302.9  854.68   322.5  860.48
#Mann= 3 , 0 , 0
       0     .06       0   146.6    .045       0   174.9     .06       0
Bank Sta=146.6,174.9
XS Rating Curve= 0 ,0
Exp/Cntr=0.3,0.1

Type RM Length L Ch R = 1 ,10989.2 ,348.3,365.7,383
XS GIS Cut Line= 4
     1619608.131      354116.612     1619521.326       354104.46
     1619368.548      354191.265     1619273.062      354371.821
#Sta/Elev= 30
       0  851.59     9.7  847.53    29.2  839.74      39  836.01    48.7  832.47
    58.4  829.36    68.2  827.16    77.9  825.88   107.2  823.05   126.7  821.32
   136.5  820.59   146.2  820.18     156  820.08   201.2  820.38   216.2  820.79
   243.8  821.91   253.6  822.78   263.4  824.85   273.1  827.58   282.8  830.09
   302.3  834.27     312  836.54   321.7  839.28   341.2  846.18   350.9  849.38
   380.1  858.75   389.8  861.71   438.4  875.46   448.2  878.16   467.6  883.77
#Mann= 3 , 0 , 0
       0     .06       0   201.2    .045       0   216.2     .06       0
Bank Sta=201.2,216.2
XS Rating Curve= 0 ,0
Exp/Cntr=0.3,0.1

Type RM Length L Ch R = 1 ,10623.5 ,179.4,175.7,172
XS GIS Cut Line= 3
     1619568.201      353903.071     1619469.242      353852.724
     1619276.534      353807.585
#Sta/Elev= 23
       0  841.63    27.8   829.7      37  826.52    46.3  825.02    55.5  824.37
   101.8  822.07   129.9   820.3   148.7  818.77     177  816.29   186.5  815.54
   195.8  815.26   201.5  816.11   205.3  816.67   214.7  819.52   224.1  823.37
     243  832.63   252.4  836.29   261.8  838.12   271.2  839.34   280.7  841.91
   290.1  845.83   299.5  849.89     309  853.84
#Mann= 3 , 0 , 0
       0     .06       0   186.5    .045       0   201.5     .07       0
Bank Sta=186.5,201.5
XS Rating Curve= 0 ,0
Exp/Cntr=0.3,0.1

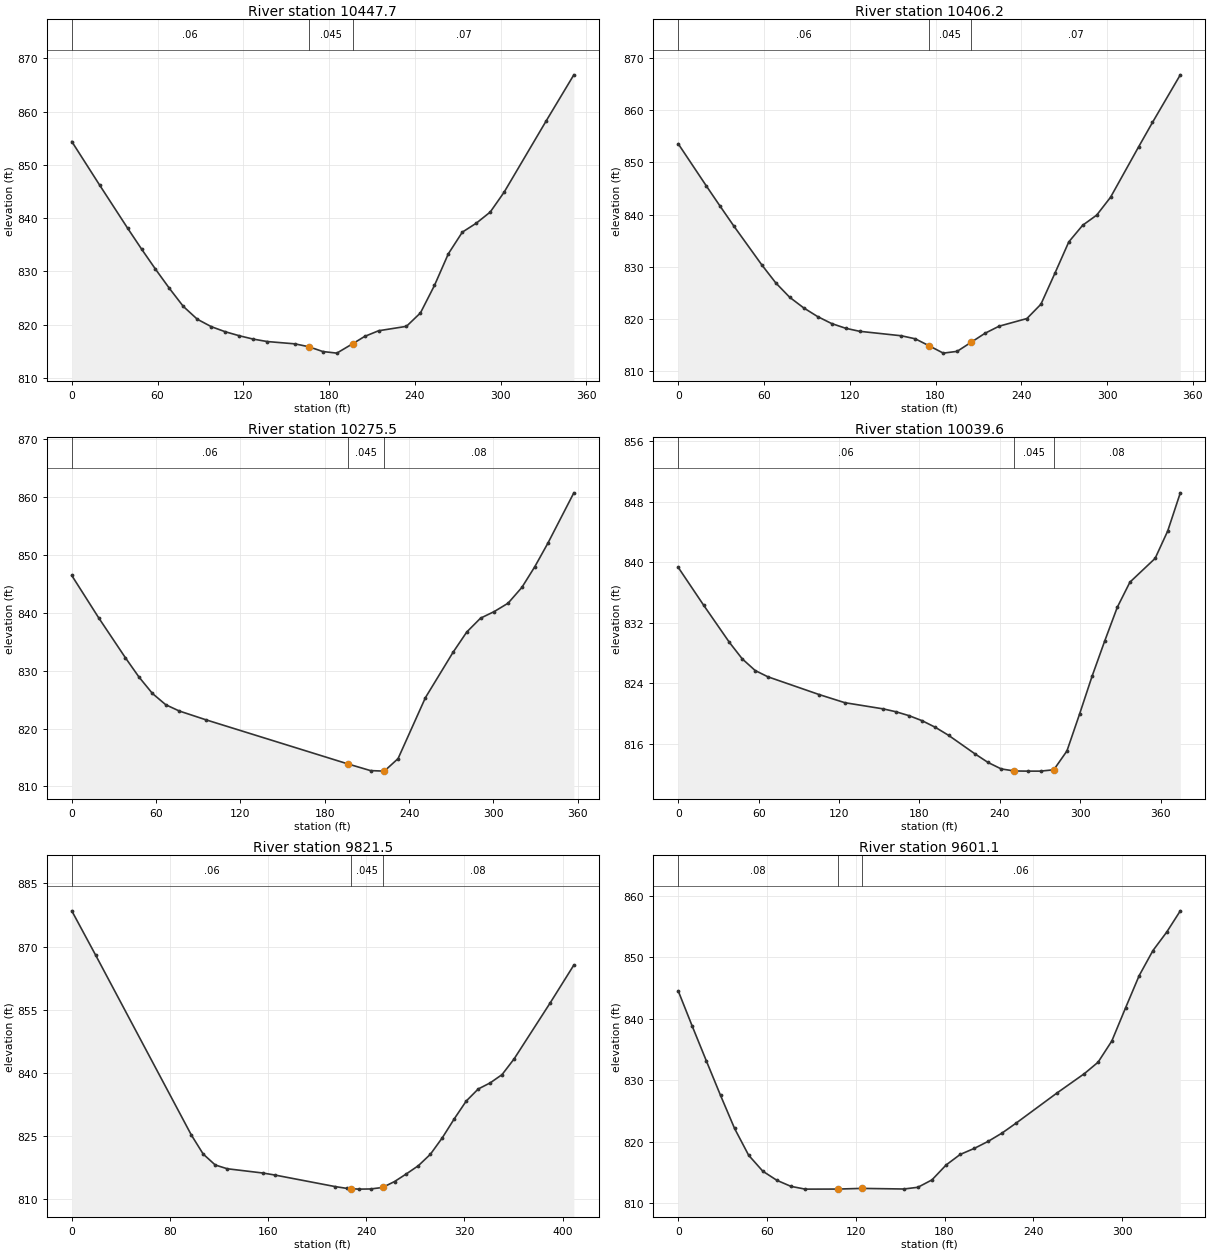
Type RM Length L Ch R = 1 ,10447.7 ,41.5,41.5,41.5
XS GIS Cut Line= 2
     1619612.254      353674.121     1619261.777      353651.335
#Sta/Elev= 30
       0  854.41    19.5  846.22      39  838.16    48.8  834.22    58.5  830.46
    68.3  826.83      78  823.45    87.8  821.04    97.6  819.64   107.3  818.69
   117.1  817.94   126.8  817.31   136.6  816.85   156.1  816.41   165.8  815.87
   175.6  814.97   185.4  814.67   196.6  816.45   204.9  817.81   214.6  818.87
   234.1   819.7   243.9  822.22   253.7  827.38   263.4  833.32   273.2  837.39
   282.9  839.06   292.7  841.16   302.4  844.88   331.7  858.21   351.2  866.93
#Mann= 3 , 0 , 0
       0     .06       0   165.8    .045       0   196.6     .07       0
Bank Sta=165.8,196.6
XS Rating Curve= 0 ,0
Exp/Cntr=0.3,0.1

Type RM Length L Ch R = 1 ,10406.2 ,126.2,130.8,135.3
XS GIS Cut Line= 2
      1619617.68      353632.888     1619267.202      353610.102
#Sta/Elev= 30
       0  853.54    19.5  845.54    29.3   841.6      39  837.76    58.5  830.35
    68.3   826.9      78  824.16    87.8  822.13    97.6  820.46   107.3  819.14
   117.1  818.24   126.8  817.66   156.1   816.8   165.8  816.22   175.6  814.87
   185.4  813.48   195.1  813.82   204.9  815.56   214.6  817.28   224.4  818.63
   243.9   820.1   253.7  822.84   263.4  828.72   273.2  834.77   282.9  837.95
   292.7  839.89   302.4  843.31     322  852.94   331.7  857.62   351.2  866.74
#Mann= 3 , 0 , 0
       0     .06       0   175.6    .045       0   204.9     .07       0
Bank Sta=175.6,204.9
XS Rating Curve= 0 ,0
Exp/Cntr=0.3,0.1

Type RM Length L Ch R = 1 ,10275.5 ,237.2,235.9,234.5
XS GIS Cut Line= 4
     1619614.425      353559.104     1619509.173      353513.531
     1619310.605      353460.362     1619279.138      353440.831
#Sta/Elev= 22
       0  846.45    19.1  839.15    38.2  832.22    47.8  828.91    57.4  826.06
    66.9  824.11    76.5  823.03    95.6   821.5   196.7  813.87   212.6  812.73
   222.4  812.64   232.2   814.8   251.7  825.35   271.3  833.16   281.1  836.68
   290.9  839.07   300.7  840.22   310.5  841.66   320.3  844.38   329.5  847.96
   338.8  852.02   357.3  860.73
#Mann= 3 , 0 , 0
       0     .06       0   196.7    .045       0   222.4     .08       0
Bank Sta=196.7,222.4
XS Rating Curve= 0 ,0
Exp/Cntr=0.3,0.1

Type RM Length L Ch R = 1 ,10039.6 ,232.3,218.1,203.1
XS GIS Cut Line= 4
     1619697.975      353371.387     1619563.426      353280.241
     1619438.643      353254.199     1619354.008      353252.029
#Sta/Elev= 30
       0  839.31    19.1  834.28    38.2   829.4    47.8  827.22    57.4  825.69
    66.9  824.86   105.2  822.51   124.3  821.44     153  820.62   162.5  820.24
   172.3  819.72   182.1  819.05   191.9  818.18   201.7  817.13   221.4  814.68
   231.2  813.54     241  812.69   250.8  812.42   260.6   812.4   270.4   812.4
   280.2  812.58     290  815.06   299.4  819.92   308.8  824.95   318.2  829.59
   327.6  834.05     337  837.36   355.8   840.5   365.2  844.12   374.6  849.16
#Mann= 3 , 0 , 0
       0     .06       0   250.8    .045       0   280.2     .08       0
Bank Sta=250.8,280.2
XS Rating Curve= 0 ,0
Exp/Cntr=0.3,0.1

Type RM Length L Ch R = 1 ,9821.5  ,221.8,220.3,219.7
XS GIS Cut Line= 2
      1619696.89       352948.21     1619322.541       353113.14
#Sta/Elev= 27
       0  878.47    19.5  867.93    97.4  825.28   107.1  820.74   116.9  818.15
   126.6  817.26   155.8  816.24   165.6  815.76   214.3  813.04     224   812.6
   227.5  812.54   233.8  812.42   243.5  812.46   253.2  812.81     263  814.22
   272.7  816.05   282.4  817.98   292.2  820.69   301.9   824.6   311.7  829.12
   321.4  833.32   331.2  836.19   340.9  837.63   350.6   839.6   360.4  843.32
   389.6  856.52   409.1   865.6
#Mann= 3 , 0 , 0
       0     .06       0   227.5    .045       0   253.2     .08       0
Bank Sta=227.5,253.2
XS Rating Curve= 0 ,0
Exp/Cntr=0.3,0.1

Type RM Length L Ch R = 1 ,9601.1  ,214.2,188.7,145.9
XS GIS Cut Line= 3
     1619560.171      352775.684     1619371.369      352866.829
     1619266.117      352942.784
#Sta/Elev= 30
       0  844.53     9.5  838.78    19.1   833.1    28.6  827.54    38.1  822.16
    47.6  817.81    57.2  815.21    66.7  813.73    76.2  812.75    85.8   812.3
   108.1  812.31   123.9  812.42   152.5  812.32     162   812.6   171.5   813.8
   181.1  816.23   190.6  817.94   200.1  818.92   209.6  820.08   218.9  821.42
   228.2     823     256  827.93   274.6  831.09   283.8  832.94   293.1  836.39
   302.4  841.79   311.6  847.03   320.9   851.1   330.2   854.1   339.4  857.56
#Mann= 3 , 0 , 0
       0     .08       0   108.1    .045       0   123.9     .06       0
Bank Sta=108.1,123.9
XS Rating Curve= 0 ,0
Exp/Cntr=0.3,0.1

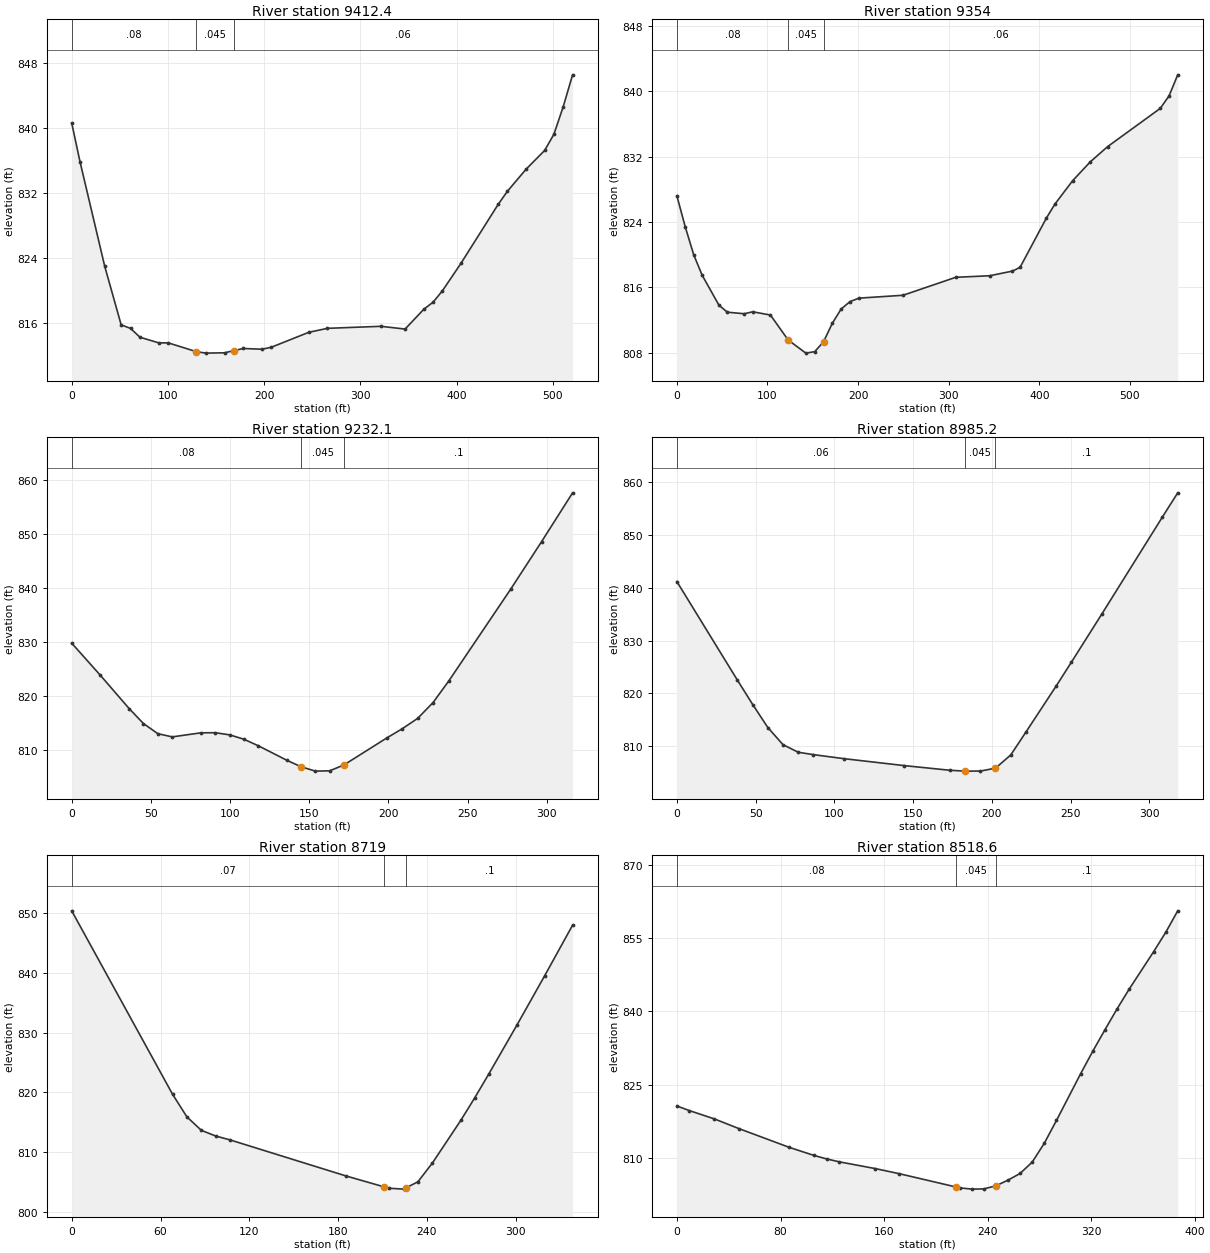
Type RM Length L Ch R = 1 ,9412.4  ,57.6,58.4,76.5
XS GIS Cut Line= 6
     1619543.085      352567.763     1619497.512      352543.891
     1619470.385      352572.103     1619440.003      352654.568
     1619403.111      352818.414     1619255.541      352910.645
#Sta/Elev= 30
       0  840.61     8.6  835.86    34.3  822.99    51.4  815.78    61.2  815.34
      71  814.25    90.6  813.56   100.4  813.56   129.6  812.48   139.4   812.3
   158.9  812.34   168.4  812.61   178.5  812.87   197.9  812.78   207.6  813.03
   246.4  814.86   265.8  815.35   321.4   815.6   346.5  815.26   365.9  817.69
   375.6  818.57   385.2  819.95   404.6  823.35   443.2  830.59   452.9  832.22
   472.2  834.92   491.6  837.24   501.2  839.23   510.9  842.63   520.6  846.54
#Mann= 3 , 0 , 0
       0     .08       0   129.6    .045       0   168.4     .06       0
Bank Sta=129.6,168.4
XS Rating Curve= 0 ,0
Exp/Cntr=0.3,0.1

Type RM Length L Ch R = 1 ,9354    ,86.6,121.9,157.2
XS GIS Cut Line= 6
      1619548.51      352544.976       1619469.3      352517.849
     1619442.173      352546.061     1619411.791      352628.526
     1619374.899      352792.372      1619227.33      352884.603
#Sta/Elev= 30
       0   827.2     9.3  823.38    18.6  819.98    27.9  817.48    46.5   813.8
    55.8  812.95    74.4  812.76    83.7     813   103.3   812.6   122.9  809.54
   142.4  807.94   152.2  808.12   161.9  809.33   171.7  811.62   181.4  813.35
   191.2  814.25     201  814.67   249.6  815.02   307.8  817.22   345.3  817.41
   370.4  817.98   378.8  818.44   407.8  824.46   417.5  826.22   436.8  829.04
   456.2  831.34   475.5  833.22   533.5  837.89   543.2  839.42   552.8     842
#Mann= 3 , 0 , 0
       0     .08       0   122.9    .045       0   161.9     .06       0
Bank Sta=122.9,161.9
XS Rating Curve= 0 ,0
Exp/Cntr=0.3,0.1

Type RM Length L Ch R = 1 ,9232.1  ,246.8,247,247.2
XS GIS Cut Line= 4
     1619555.831      352445.822     1619448.409      352463.184
     1619358.348      352465.354     1619241.161      352458.843
#Sta/Elev= 24
       0  829.78    18.1  823.83    36.3  817.66    45.3   814.9    54.4  813.02
    63.5  812.43    81.6  813.18    90.7   813.2    99.8   812.8   108.8  811.99
   117.8  810.79   135.8  808.11   144.8   806.9   153.9  806.09   162.9  806.15
   171.9  807.23   198.9  812.22   208.7  813.93   218.5  815.86   228.2  818.79
     238  822.73   277.2  839.77   296.7  848.56   316.3  857.61
#Mann= 3 , 0 , 0
       0     .08       0   144.8    .045       0   171.9      .1       0
Bank Sta=144.8,171.9
XS Rating Curve= 0 ,0
Exp/Cntr=0.3,0.1

Type RM Length L Ch R = 1 ,8985.2  ,263.2,266.2,269.1
XS GIS Cut Line= 2
     1619588.383      352215.788     1619270.458      352220.128
#Sta/Elev= 20
       0  841.16    38.5  822.48    48.2  817.88    57.8  813.53    67.4   810.3
    77.1  808.87    86.7  808.42     106  807.66   144.5  806.34   173.4  805.46
   183.1   805.3   192.7  805.31   202.3  805.86     212  808.36   221.6  812.68
   240.9  821.43   250.5  825.91   269.8  835.01   308.3  853.38     318  857.94
#Mann= 3 , 0 , 0
       0     .06       0   183.1    .045       0   202.3      .1       0
Bank Sta=183.1,202.3
XS Rating Curve= 0 ,0
Exp/Cntr=0.3,0.1

Type RM Length L Ch R = 1 ,8719    ,199.9,200.3,200.8
XS GIS Cut Line= 4
     1619635.041      352022.645      1619542.81      351968.392
     1619397.411      351951.031     1619314.945      351930.414
#Sta/Elev= 19
       0  850.35    68.1  819.69    77.8   815.9    87.6  813.64    97.3  812.69
     107  812.04   185.1  806.03     211  804.19   214.4  803.96   224.2  803.81
     226  804.04   233.9  805.04   243.7  808.18   262.9  815.32   272.3  819.08
   281.8  823.07   300.7   831.2   319.6  839.52   338.4  847.95
#Mann= 3 , 0 , 0
       0     .07       0     211    .045       0     226      .1       0
Bank Sta=211,226
XS Rating Curve= 0 ,0
Exp/Cntr=0.3,0.1

Type RM Length L Ch R = 1 ,8518.6  ,223,223,223
XS GIS Cut Line= 4
     1619671.933      351838.184     1619565.596      351771.994
     1619418.027      351751.378     1619308.435      351776.335
#Sta/Elev= 28
       0  820.62     9.6  819.68    28.9  817.98    48.2  815.96    86.7  812.16
     106  810.49   115.6  809.79   125.2   809.2   153.2  807.81   171.8  806.76
   215.6  804.04   218.4  803.87   227.7  803.61     237  803.66   246.3  804.29
   255.6  805.45   264.9  806.81   274.3  809.14   283.6  812.99     293  817.66
   311.7  827.24   321.1  831.85   330.5  836.25   339.8  840.49   349.2  844.55
   367.9  852.14   377.3  856.12   386.6  860.54
#Mann= 3 , 0 , 0
       0     .08       0   215.6    .045       0   246.3      .1       0
Bank Sta=215.6,246.3
XS Rating Curve= 0 ,0
Exp/Cntr=0.3,0.1

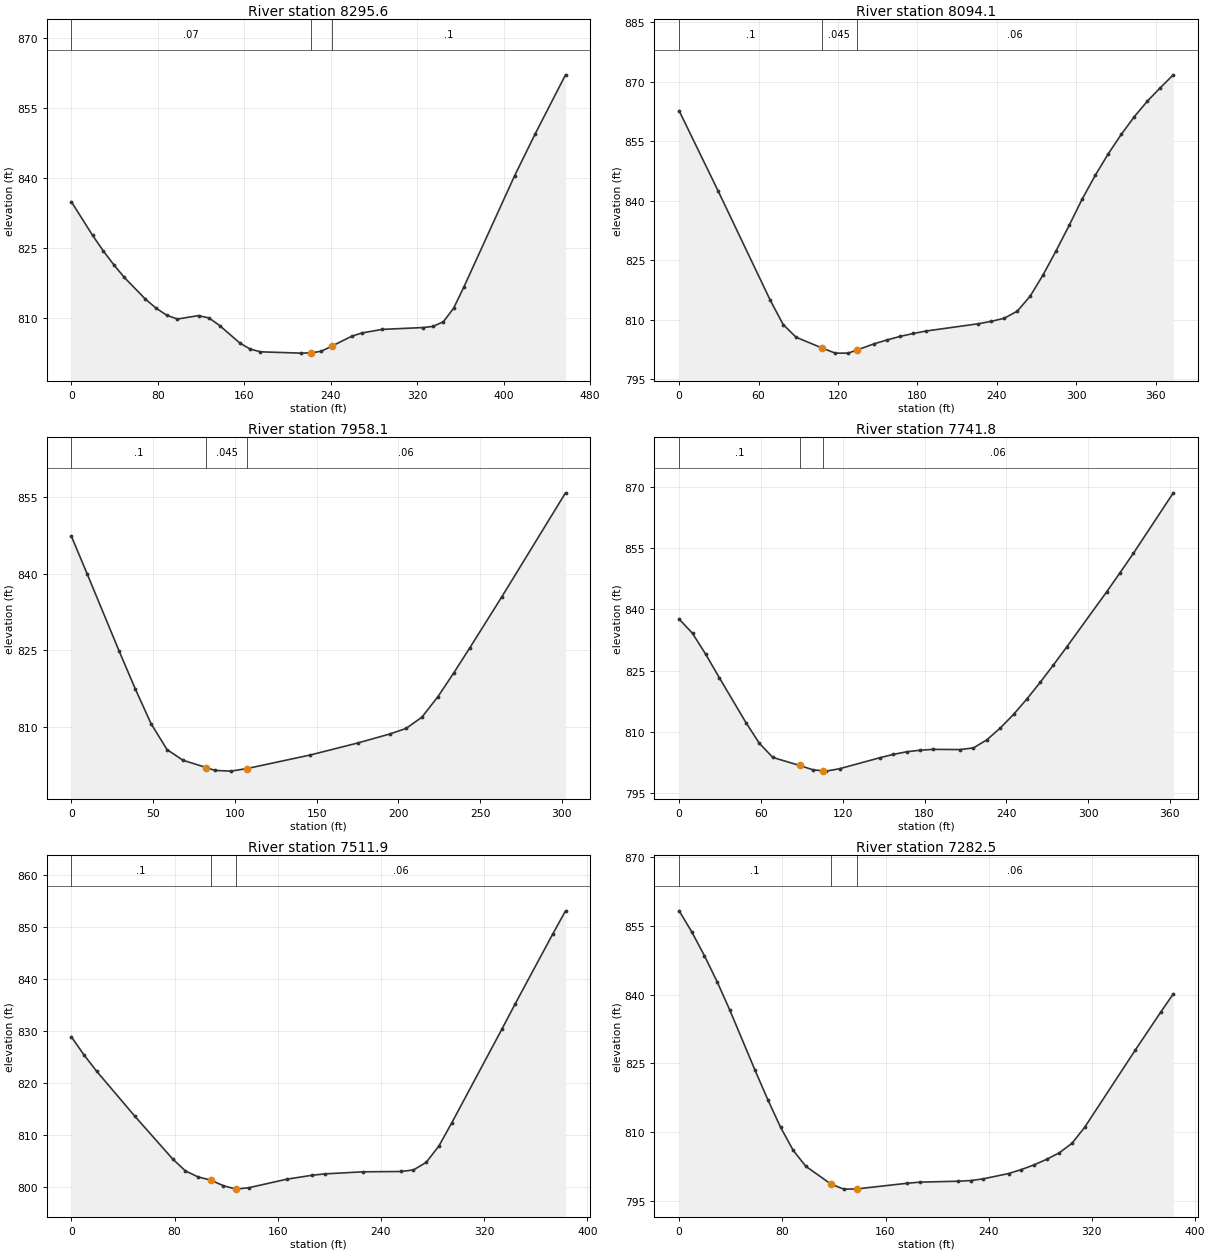
Type RM Length L Ch R = 1 ,8295.6  ,218.6,201.5,184.3
XS GIS Cut Line= 4
     1619686.039      351595.128     1619556.916       351548.47
     1619370.284      351523.513     1619259.607      351595.128
#Sta/Elev= 30
       0  834.94    19.6  827.75    29.4  824.44    39.2  821.46      49  818.72
    68.6  814.06    78.4  812.14    88.3  810.62    98.1   809.8   117.7  810.54
   127.5  810.02   137.3   808.4   156.1  804.63   165.5  803.37     175  802.78
   212.6   802.5     222  802.56   231.4  802.91   240.9  803.98   259.7  806.14
   269.1  806.83   287.9  807.59   325.6  807.98     335  808.24   344.4  809.25
   353.8  812.12   363.2  816.61   410.3  840.52   429.2  849.43   457.4  862.13
#Mann= 3 , 0 , 0
       0     .07       0     222    .045       0   240.9      .1       0
Bank Sta=222,240.9
XS Rating Curve= 0 ,0
Exp/Cntr=0.3,0.1

Type RM Length L Ch R = 1 ,8094.1  ,137,136,135
XS GIS Cut Line= 2
     1619490.727      351279.373     1619186.907      351496.387
#Sta/Elev= 30
       0  862.66    29.5  842.42    68.8  814.93    78.6  808.77    88.4  805.56
   108.1  802.84   117.9  801.56   127.7  801.56   134.1  802.31   147.4  803.92
   157.2  804.89     167  805.78   176.9  806.51   186.7  807.14     226  808.96
   235.8  809.57   245.6  810.35   255.5  812.14   265.3  815.95   275.1  821.35
   284.9  827.41   294.8  833.83   304.6  840.44   314.4  846.38   324.2  851.79
   334.1  856.72   343.9  861.16   353.7  865.06   363.5  868.44   373.4  871.73
#Mann= 3 , 0 , 0
       0      .1       0   108.1    .045       0   134.1     .06       0
Bank Sta=108.1,134.1
XS Rating Curve= 0 ,0
Exp/Cntr=0.3,0.1

Type RM Length L Ch R = 1 ,7958.1  ,216.3,216.3,216.3
XS GIS Cut Line= 2
     1619370.284      351194.737     1619132.654      351381.369
#Sta/Elev= 21
       0   847.3     9.8  839.82    29.2  824.86      39  817.52    48.7  810.69
    58.5  805.61    68.2  803.53    82.5   802.1    87.7  801.54    97.5   801.4
   107.2  801.89   146.2  804.56   175.4  806.92   194.9  808.67   204.7  809.74
   214.4  811.95   224.2  815.96   233.9  820.61   243.7  825.51   263.2  835.43
   302.2  855.76
#Mann= 3 , 0 , 0
       0      .1       0    82.5    .045       0   107.2     .06       0
Bank Sta=82.5,107.2
XS Rating Curve= 0 ,0
Exp/Cntr=0.3,0.1

Type RM Length L Ch R = 1 ,7741.8  ,231.7,229.9,227.8
XS GIS Cut Line= 3
       1619223.8      351037.402     1619045.848      351176.291
     1618975.319      351293.479
#Sta/Elev= 30
       0  837.63     9.8  834.14    19.6  828.95    29.4   823.3    49.1   812.2
    58.9  807.16    68.7  803.72    88.3  801.75    98.2  800.68   105.4  800.44
     108  800.36   117.8  800.96   147.2  803.64     157  804.45   166.8   805.1
   176.7  805.48   186.5   805.7   206.1  805.64   215.9  806.05   225.7  808.03
   235.5   810.9   245.3  814.25     255  818.01   264.8   822.1   274.6   826.4
   284.4  830.83   313.7  844.35   323.4  848.98   333.2  853.74   362.5  868.58
#Mann= 3 , 0 , 0
       0      .1       0    88.3    .045       0   105.4     .06       0
Bank Sta=88.3,105.4
XS Rating Curve= 0 ,0
Exp/Cntr=0.3,0.1

Type RM Length L Ch R = 1 ,7511.9  ,231.1,229.4,227.7
XS GIS Cut Line= 2
     1619088.166       350839.92     1618807.133      351100.336
#Sta/Elev= 24
       0  828.84     9.8  825.35    19.6  822.22    49.1   813.6    78.6  805.33
    88.4  803.06    98.2   801.9   108.1  801.28   117.9   800.2   127.7  799.55
   137.5  799.82     167  801.46   186.7  802.22   196.5  802.48     226  802.88
   255.4  802.94   265.2  803.24   275.1   804.7   284.9  807.84   294.7   812.2
     334  830.42   343.8  835.05   373.3  848.65   383.1  853.06
#Mann= 3 , 0 , 0
       0      .1       0   108.1    .045       0   127.7     .06       0
Bank Sta=108.1,127.7
XS Rating Curve= 0 ,0
Exp/Cntr=0.3,0.1

Type RM Length L Ch R = 1 ,7282.5  ,130.8,132.1,133.2
XS GIS Cut Line= 2
      1618922.15      350668.479     1618661.734      350949.512
#Sta/Elev= 28
       0   858.2     9.8  853.61    19.6  848.45    29.5  842.76    39.3   836.6
    58.9  823.49    68.8   817.1    78.6  811.15    88.4  806.12    98.2  802.65
   117.9  798.74   127.7  797.68   137.5  797.72   176.8  798.96   186.7   799.2
   216.1   799.4     226  799.54   235.8  799.92   255.4  801.07   265.2  801.93
   275.1  802.95   284.9  804.16   294.7  805.58   304.6  807.66   314.4  811.13
   353.7  827.95   373.3  836.15   383.1  840.14
#Mann= 3 , 0 , 0
       0      .1       0   117.9    .045       0   137.5     .06       0
Bank Sta=117.9,137.5
XS Rating Curve= 0 ,0
Exp/Cntr=0.3,0.1

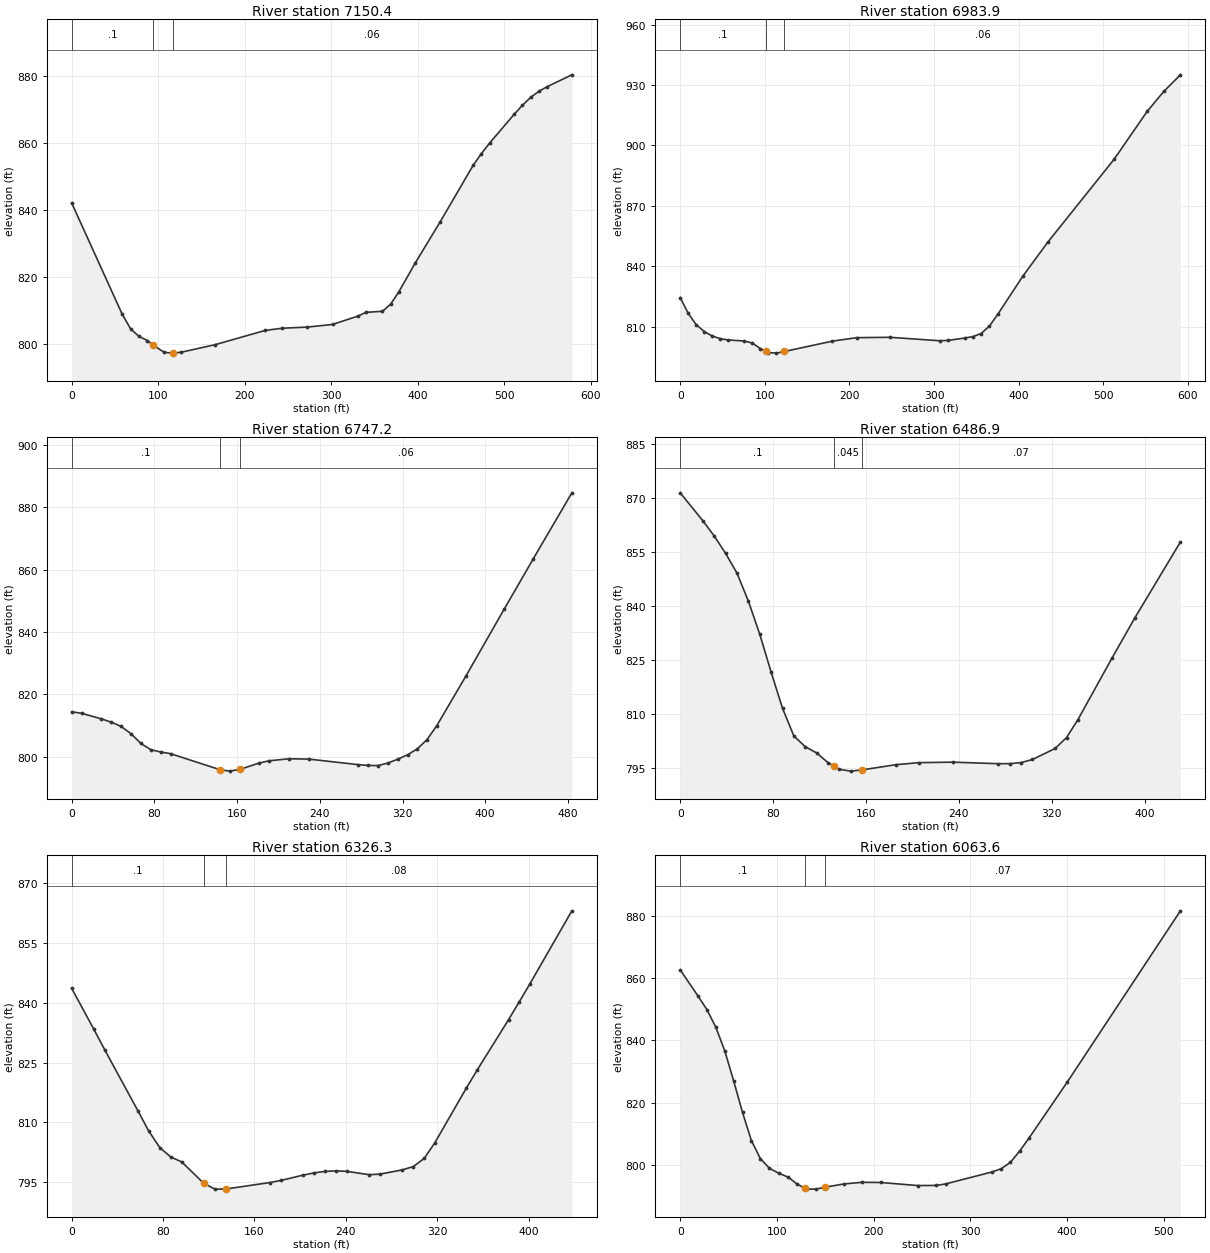
Type RM Length L Ch R = 1 ,7150.4  ,162.1,166.5,171
XS GIS Cut Line= 3
     1618821.239      350592.524     1618583.609      350822.559
     1618591.204      351069.954
#Sta/Elev= 30
       0  842.15    58.4  808.99    68.1  804.62    77.8  802.36    87.6  801.13
    94.3  799.74     107  797.61   116.7  797.38   126.5  797.64   165.4  799.87
   223.7  804.15   243.2   804.8   272.4  805.15   301.6  805.93   330.7  808.41
   340.2  809.54   359.3  809.86   368.8     812   378.3  815.71   397.4  824.36
   425.9  836.49     464  853.34   473.5  856.83     483  859.98   511.6  868.62
   521.1   871.3   530.6  873.65   540.2  875.47   549.7  876.84   578.2  880.37
#Mann= 3 , 0 , 0
       0      .1       0    94.3    .045       0   116.7     .06       0
Bank Sta=94.3,116.7
XS Rating Curve= 0 ,0
Exp/Cntr=0.3,0.1

Type RM Length L Ch R = 1 ,6983.9  ,237.2,236.7,236
XS GIS Cut Line= 3
     1618730.093      350479.677     1618562.992      350587.099
     1618176.708      350656.543
#Sta/Elev= 30
       0  824.37     9.5  816.49    18.9  810.91    28.4   807.5    37.8  805.26
    47.3  803.97    56.8  803.27    75.7  802.81    85.1   801.8    94.6  799.06
   100.8  797.75   104.1  797.05   113.5  796.76     123  797.57   179.7  802.71
   208.5  804.45   247.7  804.63   306.6  802.92   316.4  803.08     336  804.25
   345.8  804.97   355.6  806.51   365.4  810.22   375.3  816.08   404.7  834.91
   434.1  851.78   512.6  893.06   551.9  916.99   571.5   926.9   591.1  935.14
#Mann= 3 , 0 , 0
       0      .1       0   100.8    .045       0     123     .06       0
Bank Sta=100.8,123
XS Rating Curve= 0 ,0
Exp/Cntr=0.3,0.1

Type RM Length L Ch R = 1 ,6747.2  ,260.7,260.3,259.5
XS GIS Cut Line= 3
     1618627.825      350264.833     1618358.728      350447.125
     1618211.158      350505.718
#Sta/Elev= 30
       0  814.41     9.6  813.91    28.7  812.14    38.2  811.08    47.8  809.72
    57.4  807.37    66.9  804.25    76.5  802.24      86   801.5    95.6  800.97
   143.4  795.82     153  795.36   162.5   795.9   181.6  797.98   191.2  798.69
   210.3  799.32   229.4  799.22   277.2  797.44   286.8  797.18   296.4  797.14
   305.9  797.97   315.5   799.2     325  800.62   334.4  802.53   343.7  805.47
     353  809.87   381.1  825.74   418.4  847.38   446.4  863.45   483.8  884.67
#Mann= 3 , 0 , 0
       0      .1       0   143.4    .045       0   162.5     .06       0
Bank Sta=143.4,162.5
XS Rating Curve= 0 ,0
Exp/Cntr=0.3,0.1

Type RM Length L Ch R = 1 ,6486.9  ,162.2,160.6,158.8
XS GIS Cut Line= 3
     1618478.086      350059.104     1618217.669      350250.076
     1618148.224      350332.541
#Sta/Elev= 30
       0  871.43    19.6  863.63    29.4   859.4    39.1  854.61    48.9  849.14
    58.7  841.37    68.5  832.19    78.3  821.66    88.1  811.64    97.9  803.93
   107.6     801   117.4  799.25   127.2  796.57   132.8   795.5     137   794.7
   146.8  794.19   156.6  794.53   185.9  795.98   205.5  796.54   234.9  796.68
     274  796.25   283.8  796.26   293.6  796.56   303.4  797.42   322.9  800.48
   332.7   803.5   342.5  808.47   371.9  825.58   391.5  836.69   430.8  857.79
#Mann= 3 , 0 , 0
       0      .1       0   132.8    .045       0   156.6     .07       0
Bank Sta=132.8,156.6
XS Rating Curve= 0 ,0
Exp/Cntr=0.3,0.1

Type RM Length L Ch R = 1 ,6326.3  ,266.3,262.6,258.9
XS GIS Cut Line= 3
     1618338.871      349956.131     1618103.194      350155.349
     1618025.069      350258.214
#Sta/Elev= 30
       0  843.66    19.3  833.44    28.9  828.25    57.9  812.96    67.5  807.81
    77.2  803.66    86.8  801.32    96.4  800.08   115.5  794.74   125.4  793.26
     135  793.29   173.6  794.92   183.2  795.44   202.5  796.77   212.2  797.34
   221.8  797.71   231.4  797.84   241.1  797.71   260.4  796.88     270  797.03
   289.3  798.09     299  798.92   308.6  800.98   317.8  804.86   345.5  818.65
   354.7  823.04   382.4   835.8   391.6   840.2   400.9   844.7   437.8  863.11
#Mann= 3 , 0 , 0
       0      .1       0   115.5    .045       0     135     .08       0
Bank Sta=115.5,135
XS Rating Curve= 0 ,0
Exp/Cntr=0.3,0.1

Type RM Length L Ch R = 1 ,6063.6  ,304.5,306.9,309.2
XS GIS Cut Line= 4
     1618109.704      349756.912      1618075.85      349832.433
     1617909.184      350030.349     1617872.725      350202.224
#Sta/Elev= 30
       0  862.59    18.4  854.19    27.6  849.82    36.8  844.18      46  836.63
    55.2     827    64.4  816.82    73.6  807.77    82.8  802.01    92.3  798.87
   101.9  797.29   111.5  796.05   121.1  793.77   128.7  792.53   130.7   792.2
   140.3  792.19   149.8   792.8     169  793.85   188.2  794.38   207.3  794.32
   245.7  793.34   264.8  793.38   274.4  793.86   322.3  797.69   331.9  798.75
   341.5   800.8   351.3  804.54     361  808.74   400.1  826.51   517.2  881.54
#Mann= 3 , 0 , 0
       0      .1       0   128.7    .045       0   149.8     .07       0
Bank Sta=128.7,149.8
XS Rating Curve= 0 ,0
Exp/Cntr=0.3,0.1

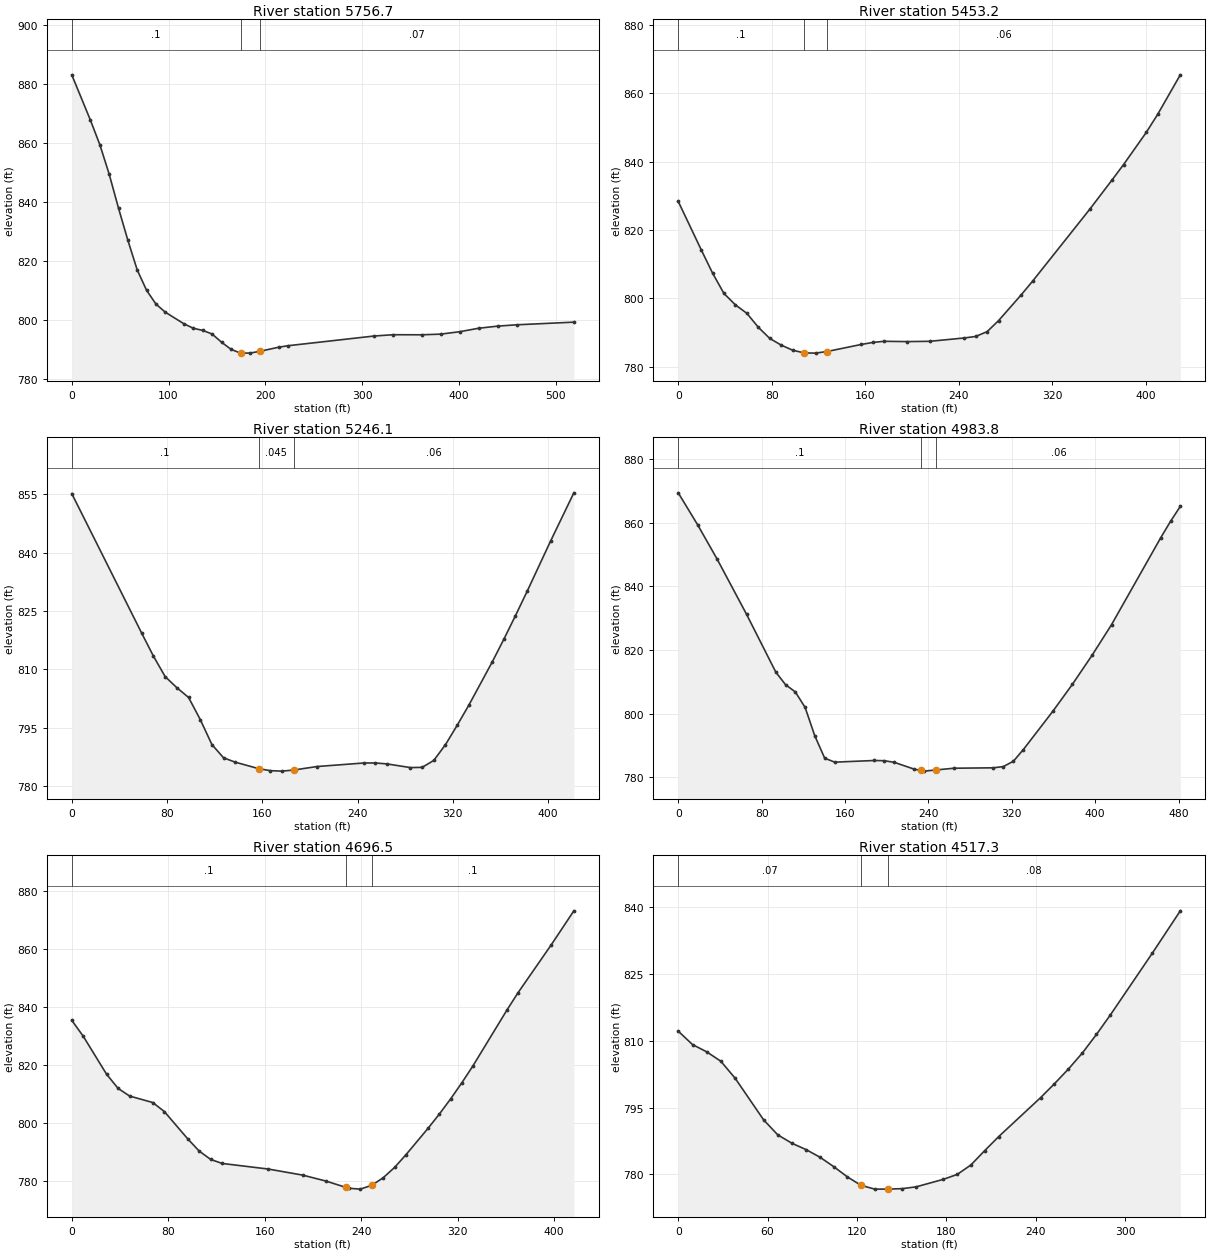
Type RM Length L Ch R = 1 ,5756.7  ,297.8,303.5,309
XS GIS Cut Line= 3
     1617867.517       349599.36     1617791.996      349723.058
     1617528.975      349988.683
#Sta/Elev= 30
       0  883.13    19.3  867.73      29  859.43    38.6  849.49    48.3  837.88
      58  826.96    67.6  816.96    77.3  810.03      87  805.36    96.6  802.62
   115.9  798.68   125.6  797.16   135.3  796.44   144.9  795.23   154.8  792.42
   164.6     790   174.4  788.73   184.3  788.76   194.1  789.33   213.8  790.74
   223.6  791.25   312.2  794.53   331.8  794.97   361.4  794.95     381  795.17
   400.7  795.99   420.4  797.17     440  797.89   459.7  798.34   518.7  799.24
#Mann= 3 , 0 , 0
       0      .1       0   174.4    .045       0   194.1     .07       0
Bank Sta=174.4,194.1
XS Rating Curve= 0 ,0
Exp/Cntr=0.3,0.1

Type RM Length L Ch R = 1 ,5453.2  ,207.9,207.1,206.3
XS GIS Cut Line= 3
     1617666.996      349467.849     1617403.975      349618.891
     1617282.882      349654.047
#Sta/Elev= 30
       0  828.35    19.6  814.24    29.4  807.36    39.1  801.42    48.9  798.09
    58.7  795.62    68.5  791.54    78.3  788.27    88.1  786.32    97.8  784.84
   107.6  784.05   117.4  783.98   127.2  784.45   156.5  786.51   166.3   787.1
   176.1  787.44   195.7  787.35   215.2  787.44   244.6  788.41   254.4  788.86
   264.2  790.27     274   793.5   293.5  801.09   303.3  805.13   351.8  825.99
   371.2   834.7   380.9  839.14   400.3  848.54     410  853.79   429.4  865.37
#Mann= 3 , 0 , 0
       0      .1       0   107.6    .045       0   127.2     .06       0
Bank Sta=107.6,127.2
XS Rating Curve= 0 ,0
Exp/Cntr=0.3,0.1

Type RM Length L Ch R = 1 ,5246.1  ,258.2,262.3,266.5
XS GIS Cut Line= 2
     1617592.777      349266.026     1617234.704      349488.683
#Sta/Elev= 30
       0  855.16    58.8  819.25    68.6  813.38    78.4  808.14    88.2  805.29
    98.1  802.77   107.9  797.09   117.7  790.66   127.5  787.25   137.3  786.14
   156.9  784.48   166.7  783.96   176.5  783.84   186.3  784.12   205.9  785.02
   245.2  785.93     255  785.94   264.8  785.69   284.4  784.75   294.2  784.81
     304  786.59   313.8  790.64   323.6   795.6   333.4  800.78     353  811.86
   362.8  817.72   372.6  823.81   382.4  830.06     402  842.92   421.6  855.36
#Mann= 3 , 0 , 0
       0      .1       0   156.9    .045       0   186.3     .06       0
Bank Sta=156.9,186.3
XS Rating Curve= 0 ,0
Exp/Cntr=0.3,0.1

Type RM Length L Ch R = 1 ,4983.8  ,283.7,287.3,290.8
XS GIS Cut Line= 4
     1617535.486      349077.224     1617406.579      349100.662
     1617220.382      349173.579     1617094.079       349255.61
#Sta/Elev= 30
       0  869.37    18.7  859.28    37.4   848.5    65.5  831.25    93.6  813.07
   102.9  809.14   112.3  806.85   121.7  801.99     131  793.06   140.5  786.04
   150.1   784.8   188.2  785.32   197.7  785.25   207.2  784.74   226.2  782.62
   232.7  782.19   235.8  781.98   247.7  782.36   264.3  782.89   302.4  783.02
   311.9  783.42   321.5  785.09     331  788.74   359.2  800.72     378   809.2
   396.9  818.33   415.7  828.01   462.8  855.26   472.2  860.41   481.6  865.12
#Mann= 3 , 0 , 0
       0      .1       0   232.7    .045       0   247.7     .06       0
Bank Sta=232.7,247.7
XS Rating Curve= 0 ,0
Exp/Cntr=0.3,0.1

Type RM Length L Ch R = 1 ,4696.5  ,174.3,179.2,184
XS GIS Cut Line= 4
     1617449.548      348861.079     1617315.434      348851.964
     1617185.225       348880.61     1617036.788      348885.818
#Sta/Elev= 30
       0  835.47     9.6  829.91    28.8  816.95    38.4  812.03      48  809.39
    67.2  807.16    76.8  804.04      96  794.74   105.6  790.49   115.2  787.58
   124.8   786.2     163  784.28   191.6  782.18   210.6  780.16   227.5  777.95
   229.6  777.68   239.2  777.37   248.7  778.67   258.2  781.28   267.8  784.89
     277  789.16   295.6  798.39   304.9  803.27   314.2  808.45   323.4  813.95
   332.7  819.82   360.6  838.84   369.9  844.88   397.7  861.51   416.3  873.13
#Mann= 3 , 0 , 0
       0      .1       0   227.5    .045       0   248.7      .1       0
Bank Sta=227.5,248.7
XS Rating Curve= 0 ,0
Exp/Cntr=0.3,0.1

Type RM Length L Ch R = 1 ,4517.3  ,176.6,176.6,176.5
XS GIS Cut Line= 4
     1617400.069      348711.339     1617314.132      348712.641
      1617194.34      348713.943     1617073.246      348764.724
#Sta/Elev= 30
       0  812.18     9.6  809.16    19.1  807.54    28.6  805.42    38.2  801.61
    57.3  792.27    66.8  788.89    76.4  786.99      86  785.55    95.2  783.86
   104.4  781.75   113.6  779.44   122.8  777.54     132   776.7     141  776.71
   150.4  776.81   159.7  777.21   178.1  778.91   187.3     780   196.5  782.12
   205.8  785.36   215.1  788.48   243.3  797.25   252.6  800.37     262  803.68
   271.4   807.3   280.8  811.44   290.2  815.85   318.3  829.69   337.1   839.2
#Mann= 3 , 0 , 0
       0     .07       0   122.8    .045       0     141     .08       0
Bank Sta=122.8,141
XS Rating Curve= 0 ,0
Exp/Cntr=0.3,0.1