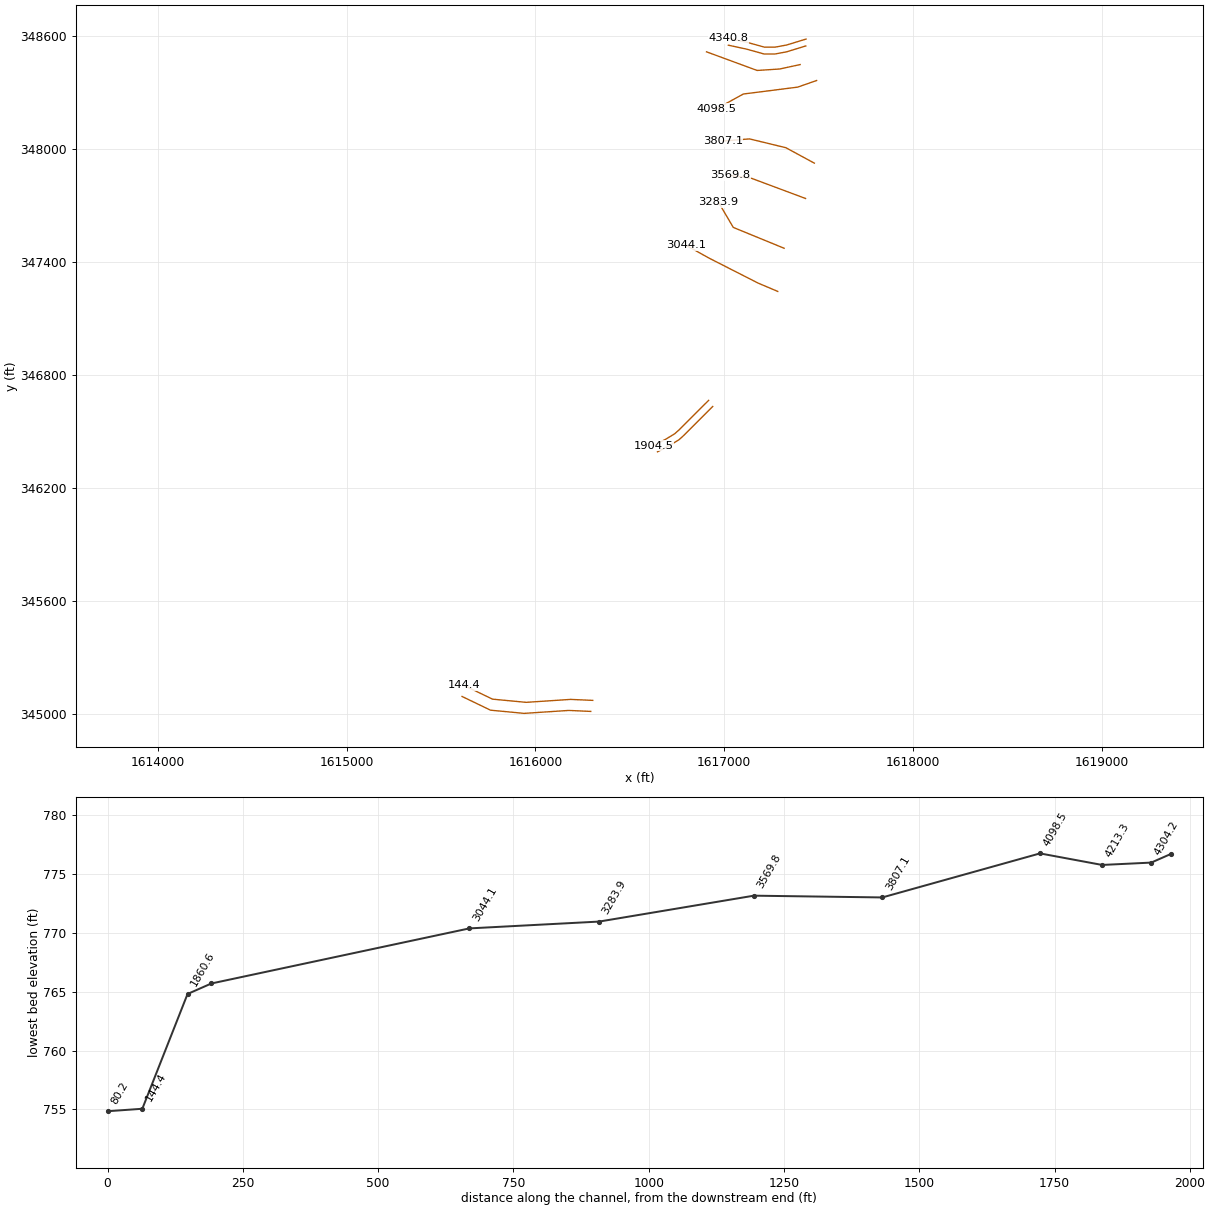
HEC-RAS study WLNUTFRK.prj: WLNUTFRK

--- WLNUTFRK.g02 (geometry) --- (continued)

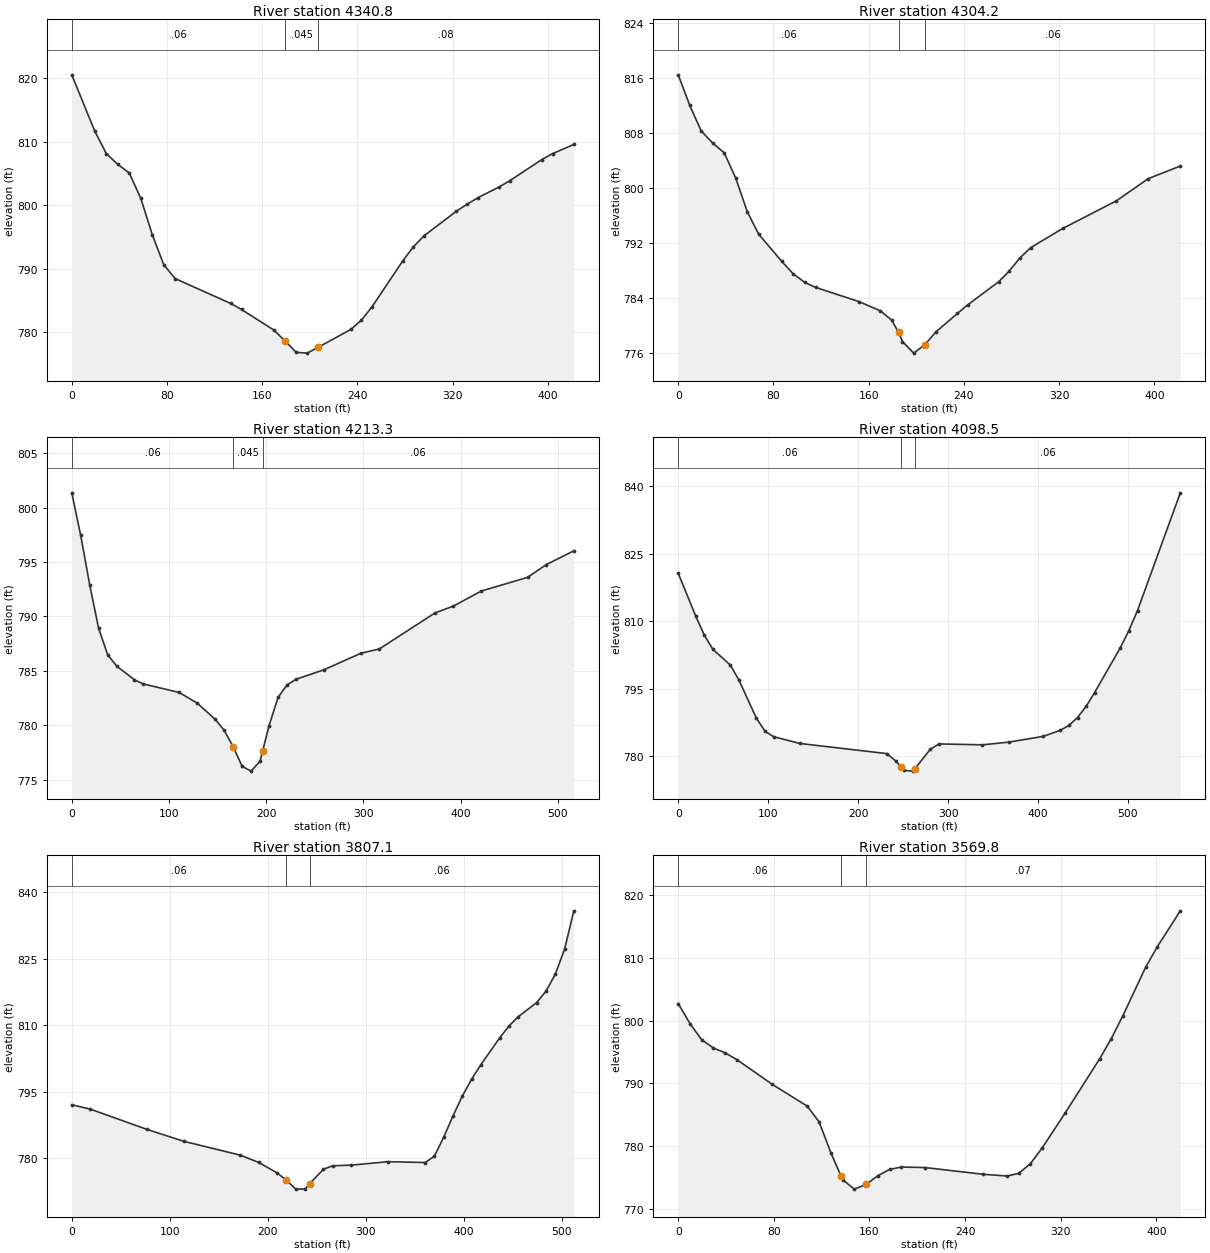
Type RM Length L Ch R = 1 ,4340.8  ,36.6,36.6,36.6
XS GIS Cut Line= 6
     1617433.923      348585.037     1617332.361      348553.787
     1617269.861      348542.068     1617213.871      348542.068
     1617120.121       348568.11     1617023.767      348588.943
#Sta/Elev= 30
       0  820.52    19.3  811.67      29  808.13    38.6  806.43    48.3  805.07
      58  801.07    67.6  795.38    77.3  790.62    86.9  788.44   133.5  784.53
   142.6  783.58   169.8  780.34   179.2  778.61   188.5  776.84   197.8  776.71
   207.2  777.65   234.5  780.45   243.2  781.88   251.9  783.91     278  791.21
     287  793.45   296.1   795.2   323.2  799.06   332.2  800.16   341.2  801.18
   359.1  802.87   368.1  803.87   394.9  807.18   403.9  808.11   421.8  809.56
#Mann= 3 , 0 , 0
       0     .06       0   179.2    .045       0   207.2     .08       0
Bank Sta=179.2,207.2
XS Rating Curve= 0 ,0
Exp/Cntr=0.3,0.1

Type RM Length L Ch R = 1 ,4304.2  ,89.2,90.8,92.3
XS GIS Cut Line= 6
     1617432.621      348548.579     1617331.059      348517.329
     1617268.559       348505.61     1617212.569       348505.61
     1617118.819      348531.651     1617022.465      348552.485
#Sta/Elev= 30
       0  816.49     9.7  812.03    19.3  808.32      29  806.54    38.6  805.14
    48.3  801.45      58  796.56    67.6  793.28    86.9  789.34    96.6  787.52
   106.3  786.26   115.4  785.54   151.7  783.48   169.8  782.13   179.2   780.8
  185.12  778.99   188.4  777.66   197.8  775.97   207.2  777.21   216.5  779.06
   234.5  781.74   243.2     783   269.3  786.38     278   787.9     287  789.82
   296.1  791.33   323.2  794.14   368.1  798.14   394.9  801.38   421.8  803.21
#Mann= 3 , 0 , 0
       0     .06       0  185.12    .045       0   207.2     .06       0
Bank Sta=185.12,207.2
XS Rating Curve= 0 ,0
Exp/Cntr=0.3,0.1

Type RM Length L Ch R = 1 ,4213.3  ,113.1,114.8,115.7
XS GIS Cut Line= 4
     1617402.673       348449.62       1617294.6      348426.183
     1617174.809       348418.37     1616906.579      348517.329
#Sta/Elev= 30
       0  801.35     9.2  797.43    18.4  792.92    27.6   788.9    36.9  786.48
    46.1  785.43    64.5  784.16    73.7  783.78   110.6     783     129  782.02
   147.5  780.54   156.8  779.52     166  778.02   175.2  776.22   184.5  775.77
   193.7  776.69   196.4  777.64   202.9  779.93   212.2  782.55   221.4  783.69
   230.6  784.21   259.2  785.08   297.3   786.6   316.4     787   373.6  790.31
   392.6  790.94   421.2  792.32   468.9  793.58   487.9  794.74   516.5  796.02
#Mann= 3 , 0 , 0
       0     .06       0     166    .045       0   196.4     .06       0
Bank Sta=166,196.4
XS Rating Curve= 0 ,0
Exp/Cntr=0.3,0.1

Type RM Length L Ch R = 1 ,4098.5  ,299.9,291.4,283
XS GIS Cut Line= 4
     1617489.913      348364.985     1617389.652      348329.829
     1617101.892       348293.37     1616959.965      348215.245
#Sta/Elev= 30
       0  820.67    19.3  811.22      29  806.92    38.6  803.77      58  800.28
    67.6  796.92    86.9  788.51    96.6  785.57   106.2  784.38   135.2  782.89
   231.9  780.64   241.6  779.05   248.2  777.59   251.3   776.9   260.9  776.75
   263.2   777.3   280.3   781.6     290  782.79   338.3  782.59   367.3  783.18
   405.8  784.46   424.9  785.82   434.4  786.89     444  788.65   453.5   791.1
     463  794.18   491.6  804.14   501.1  807.95   510.7   812.4   558.3  838.52
#Mann= 3 , 0 , 0
       0     .06       0   248.2    .045       0   263.2     .06       0
Bank Sta=248.2,263.2
XS Rating Curve= 0 ,0
Exp/Cntr=0.3,0.1

Type RM Length L Ch R = 1 ,3807.1  ,240,237.3,234.9
XS GIS Cut Line= 4
     1617478.194      347926.183     1617327.152      348008.214
     1617134.444      348055.089     1616992.517       348043.37
#Sta/Elev= 30
       0  792.04    19.1  791.04    76.4  786.51   114.6  783.78   171.9  780.68
   190.8  779.04   209.7  776.65   219.1  775.03   228.5  773.04     238  773.01
   242.8  774.22   256.9  777.48   266.3  778.28   285.2  778.42     323   779.2
   360.8  779.01   370.2  780.43   379.7   784.7   389.2  789.52   398.7  793.97
   408.2  797.81   417.7  801.09   436.7  807.07   446.2  809.77   455.6  811.86
   474.6  815.08   484.1  817.64   493.6  821.45   503.1  827.11   512.6  835.78
#Mann= 3 , 0 , 0
       0     .06       0   219.1    .045       0   242.8     .06       0
Bank Sta=219.1,242.8
XS Rating Curve= 0 ,0
Exp/Cntr=0.3,0.1

Type RM Length L Ch R = 1 ,3569.8  ,286.6,286,285.3
XS GIS Cut Line= 3
     1617431.319      347738.683     1617146.163      347845.454
     1617031.579      347861.079
#Sta/Elev= 30
       0  802.72     9.8  799.53    19.6  796.96    29.5  795.63    39.3  794.87
    49.1  793.78    78.6  789.86     108  786.37   117.9  783.87   127.7  778.96
   136.3   775.2   137.5  774.68   147.3  773.16   157.2   773.9     167   775.3
   176.8  776.29   186.6  776.68   206.3   776.6   255.4  775.52     275  775.25
   284.8  775.66   294.7  777.22   304.5  779.72   323.8   785.3   352.7  793.95
   362.3  797.11     372  800.77   391.2  808.54   400.9  811.79   420.1  817.49
#Mann= 3 , 0 , 0
       0     .06       0   136.3    .045       0   157.2     .07       0
Bank Sta=136.3,157.2
XS Rating Curve= 0 ,0
Exp/Cntr=0.3,0.1

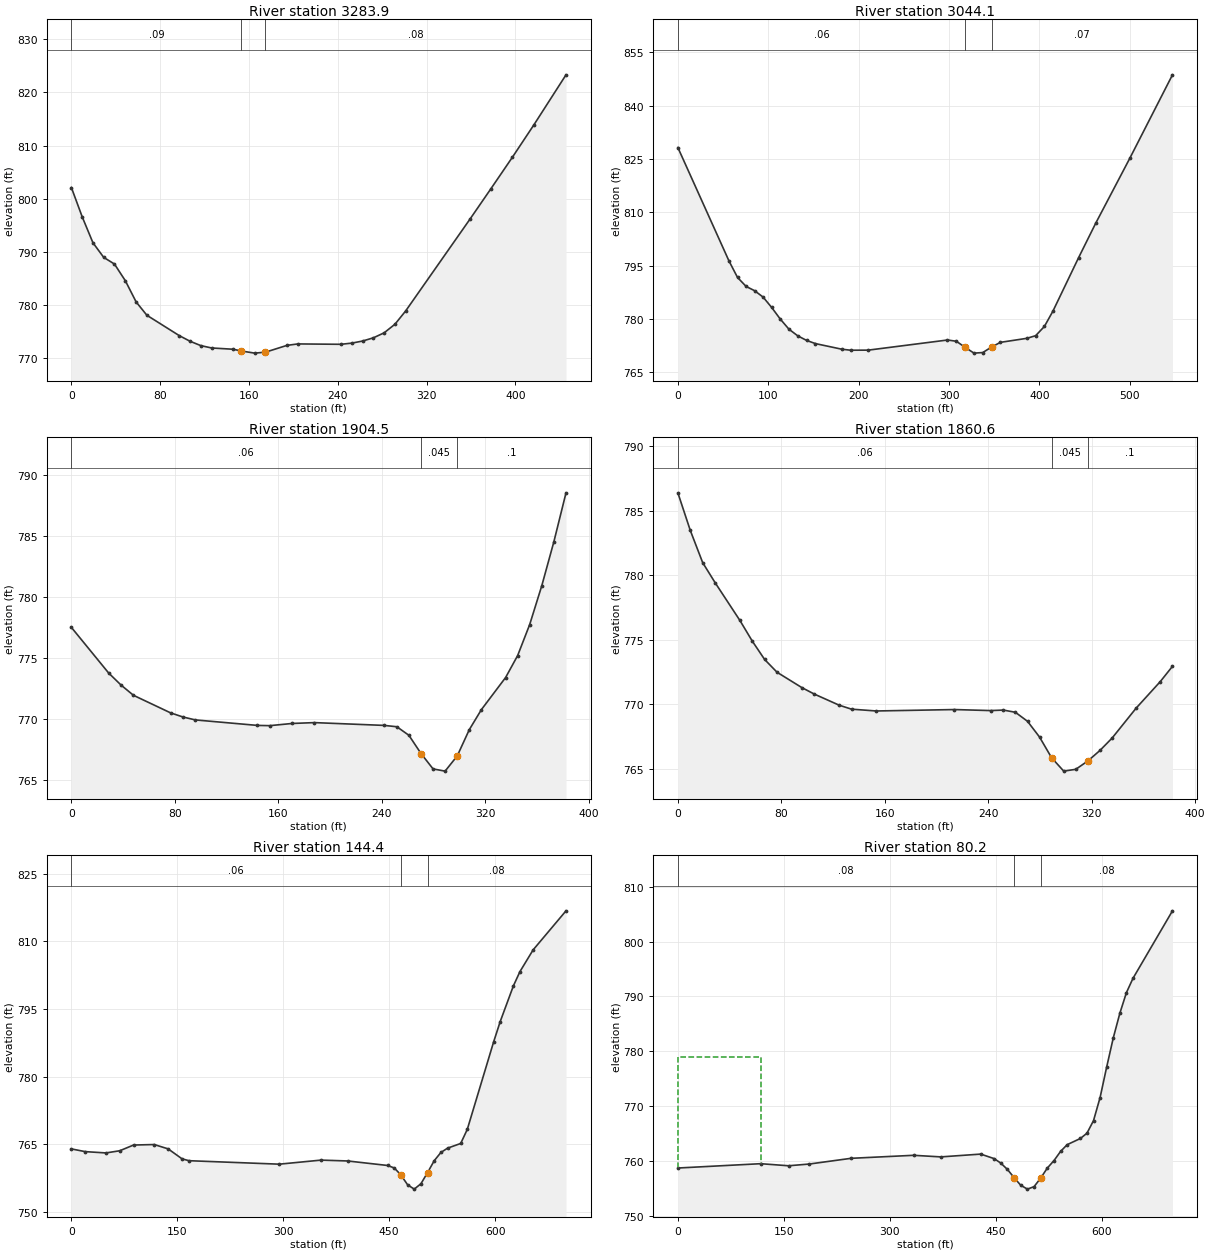
Type RM Length L Ch R = 1 ,3283.9  ,241.4,239.8,238.1
XS GIS Cut Line= 3
     1617318.038       347474.36     1617048.507      347585.037
     1616970.382      347717.849
#Sta/Elev= 30
       0   802.1     9.7  796.61    19.4  791.72    29.1  788.97    38.8  787.71
    48.6  784.57    58.3  780.59      68  778.08    97.1  774.26   106.8   773.2
   116.6  772.37   126.3  771.93   145.7  771.69   153.1  771.36   165.1  770.96
   174.8  771.14   194.2  772.42     204  772.69   242.8  772.62   252.5  772.84
   262.2  773.23     272  773.84   281.7  774.78   291.4  776.39     301  778.87
   358.8   796.1     378  801.92   397.3  807.83   416.6   813.9   445.5   823.3
#Mann= 3 , 0 , 0
       0     .09       0   153.1    .045       0   174.8     .08       0
Bank Sta=153.1,174.8
XS Rating Curve= 0 ,0
Exp/Cntr=0.3,0.1

Type RM Length L Ch R = 1 ,3044.1  ,477.6,476.8,475.4
XS GIS Cut Line= 4
     1617284.184      347245.193     1617180.017      347289.464
       1616919.6      347422.276     1616795.902      347491.287
#Sta/Elev= 30
       0  828.21    56.6  796.28      66  791.67    75.5  789.14    84.9  787.94
    94.3  786.14   103.8  783.22   113.2  779.99   122.9  777.11   132.7  775.23
   142.4  773.96   152.2  773.06   181.4  771.48   191.1   771.2   210.6  771.22
   298.3  774.07   308.1  773.72   317.8  772.01   327.6  770.38   337.3  770.54
     347  772.08   356.8  773.41     386  774.54   395.8  775.28   405.5  777.88
     415  782.22   443.3  797.21   462.2  806.88   499.9  825.14   547.2  848.66
#Mann= 3 , 0 , 0
       0     .06       0   317.8    .045       0     347     .07       0
Bank Sta=317.8,347
XS Rating Curve= 0 ,0
Exp/Cntr=0.3,0.1

Type RM Length L Ch R = 1 ,1904.5  ,48.5,43.9,43.2
XS GIS Cut Line= 6
     1616917.955      346667.068     1616809.448      346558.561
      1616760.62      346509.733     1616738.918      346490.202
     1616691.175      346460.905     1616624.986      346426.183
#Sta/Elev= 26
       0  777.49    28.8  773.75    38.4  772.76      48  771.92    76.7  770.48
    86.3  770.14    95.9   769.9   143.9  769.45   153.4  769.43   170.7  769.61
     188  769.68     242  769.45   251.7  769.34     261  768.64   270.4  767.14
   279.7  765.88     289   765.7   298.4  766.95   307.7   769.1   317.1  770.75
   335.8  773.38   345.1  775.18   354.4  777.72   363.8  780.92   373.1  784.51
   382.5  788.53
#Mann= 3 , 0 , 0
       0     .06       0   270.4    .045       0   298.4      .1       0
Bank Sta=270.4,298.4
XS Rating Curve= 0 ,0
Exp/Cntr=0.3,0.1

Type RM Length L Ch R = 1 ,1860.6  ,102.2,83.6,65.4
XS GIS Cut Line= 6
     1616939.656      346634.516     1616831.149      346526.009
     1616782.321      346477.181      1616760.62       346457.65
     1616712.877      346428.353     1616646.687      346393.631
#Sta/Elev= 28
       0  786.37     9.6  783.46    19.2  780.96    28.8  779.41      48  776.48
    57.5  774.89    67.1  773.46    76.7  772.47    95.9  771.28   105.5  770.78
   124.7  769.92   134.3  769.61   153.4  769.47   213.9  769.58     242   769.5
   251.7  769.54     261  769.37   270.4  768.67   279.7  767.45     289  765.85
   298.4  764.81   307.7  764.95   317.1   765.6   326.4  766.41   335.8  767.37
   354.4  769.69   373.1  771.75   382.5  772.93
#Mann= 3 , 0 , 0
       0     .06       0     289    .045       0   317.1      .1       0
Bank Sta=289,317.1
XS Rating Curve= 0 ,0
Exp/Cntr=0.3,0.1

Type RM Length L Ch R = 1 ,144.4   ,64,64.2,64.7
XS GIS Cut Line= 5
     1616303.719      345073.969     1616186.531      345079.178
     1615950.854      345063.553     1615772.469       345080.48
     1615621.427      345153.396
#Sta/Elev= 30
       0  763.97    19.6  763.37    48.9  763.08    68.4  763.56      88  764.83
   117.3  764.94     137  763.98   156.7  761.77   166.5  761.36   294.4  760.59
   353.5  761.49   391.2   761.3   447.8   760.3   457.2  759.75   466.1   758.3
   476.1  756.02   485.5  755.06     495  756.26   504.4  758.74   513.8  761.36
   523.2  763.18   532.7  764.14   551.3  765.18   560.6   768.3   597.9  787.68
   607.2  792.18   625.9   800.1   635.2  803.27   653.8  808.07   700.4  816.73
#Mann= 3 , 0 , 0
       0     .06       0   466.1    .045       0   504.4     .08       0
Bank Sta=466.1,504.4
XS Rating Curve= 0 ,0
Exp/Cntr=0.3,0.1

Type RM Length L Ch R = 1 ,80.2    ,96,80.2,64.4
XS GIS Cut Line= 5
     1616293.302      345015.375     1616176.114      345020.584
     1615940.437      345004.959     1615762.052      345021.886
      1615611.01      345094.803
#Sta/Elev= 30
       0   758.7   117.3  759.49   156.7  759.11   186.2  759.43   245.2  760.47
   333.8  761.02   372.4  760.73   428.9  761.24   447.8  760.42   457.2  759.61
   466.7  758.44   476.1  756.95   485.5  755.56     495  754.85   504.4   755.3
   513.8  756.87   523.2   758.7   532.7  760.07     542  761.74   551.3  762.96
     570  764.09   579.3  765.05   588.6  767.35   597.9  771.56   607.2  777.11
   616.6  782.45   625.9  786.94   635.2   790.7   644.5  793.31   700.4  805.62
#Mann= 3 , 0 , 0
       0     .08       0   476.1    .045       0   513.8     .08       0
#XS Ineff= 2 , 0
          117.63  778.87
Permanent Ineff=
       F       F
Bank Sta=476.1,513.8
XS Rating Curve= 0 ,0
Exp/Cntr=0.3,0.1